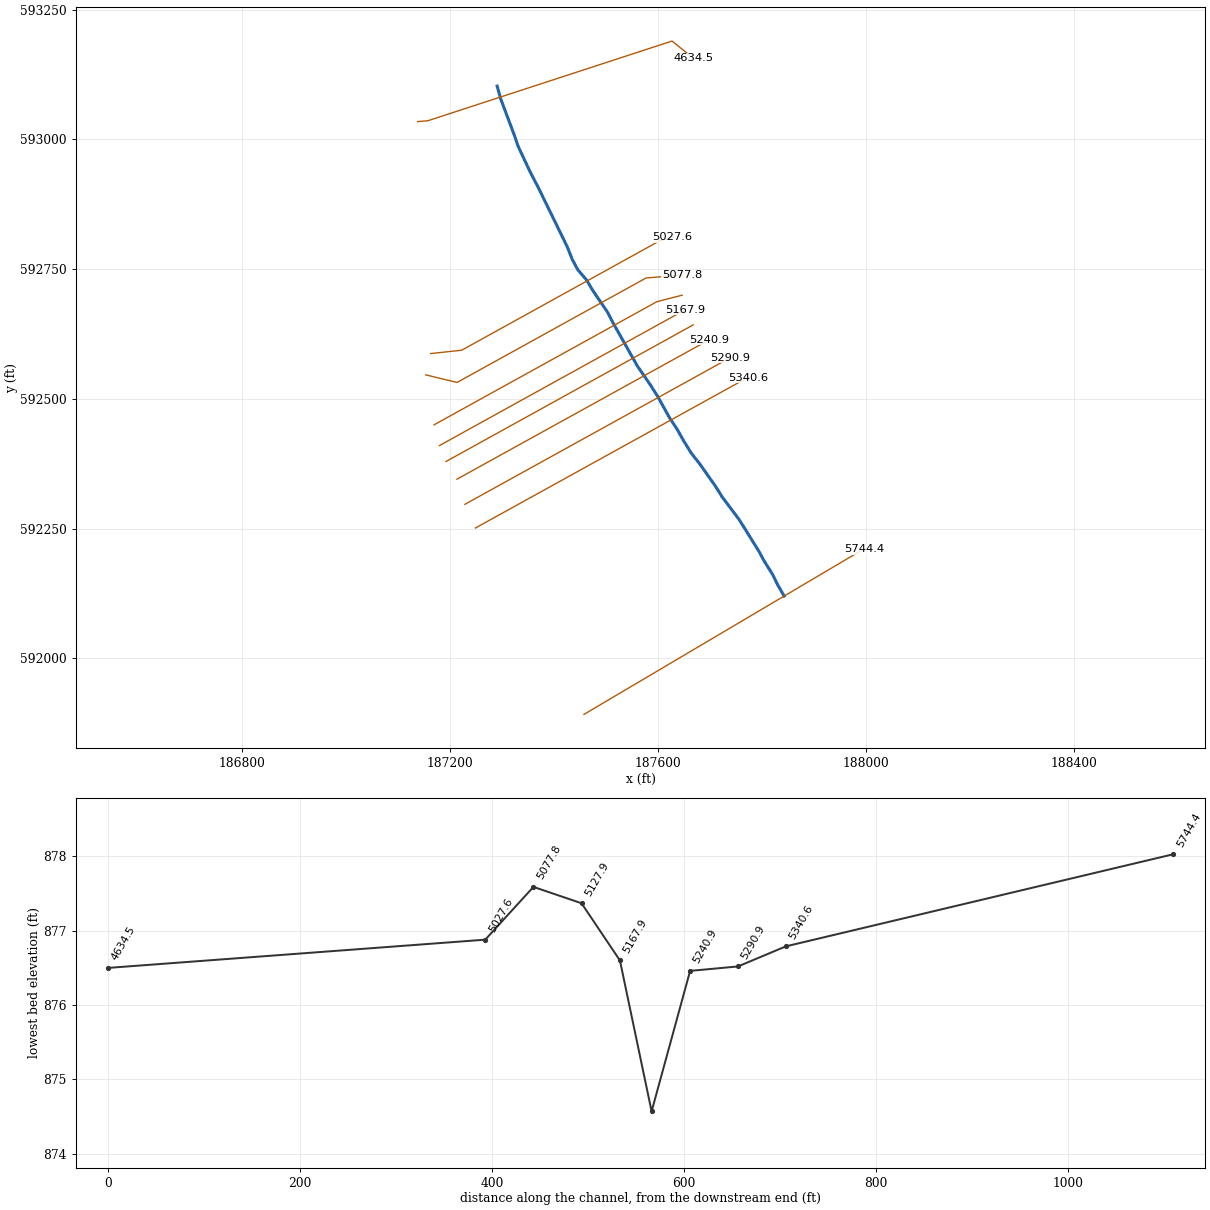
--- Wheeling Creek.prj (project) ---

Proj Title=119483_BEL_TR428-0.30 WHEELING CREEK
Current Plan=p20
Default Exp/Contr=0.3,0.1
English Units
Geom File=g01
Geom File=g02
Geom File=g03
Geom File=g04
Geom File=g05
Geom File=g06
Geom File=g07
Geom File=g08
Geom File=g09
Geom File=g10
Geom File=g11
Geom File=g12
Geom File=g13
Geom File=g14
Geom File=g15
Geom File=g16
Geom File=g17
Geom File=g18
Flow File=f01
Flow File=f02
Flow File=f03
Plan File=p01
Plan File=p02
Plan File=p03
Plan File=p04
Plan File=p05
Plan File=p06
Plan File=p07
Plan File=p08
Plan File=p09
Plan File=p10
Plan File=p11
Plan File=p12
Plan File=p13
Plan File=p14
Plan File=p15
Plan File=p16
Plan File=p17
Plan File=p19
Plan File=p18
Plan File=p20
Y Axis Title=Elevation
X Axis Title(PF)=Main Channel Distance
X Axis Title(XS)=Station
BEGIN DESCRIPTION:
Wheeling Creek
END DESCRIPTION:
DSS Export Rating Curves= 0
DSS Export Rating Curve Sorted= 0
DSS Export Volume Flow Curves= 0
DXF OffsetX= 0
DXF OffsetY= 0
DXF ScaleX= 1
DXF ScaleY= 10

--- Wheeling Creek.p20 (plan) ---

Plan Title=TAF
Program Version=6.20
Short Identifier=TAF
Geom File=g18
Flow File=f01
Subcritical Flow
K Sum by GR= 0
Std Step Tol= 0.01
Critical Tol= 0.01
Num of Std Step Trials= 20
Max Error Tol= 0.3
Flow Tol Ratio= 0.001
Split Flow NTrial= 30
Split Flow Tol= 0.02
Split Flow Ratio= 0.02
Log Output Level= 0
Friction Slope Method= 1
Unsteady Friction Slope Method= 2
Unsteady Bridges Friction Slope Method= 1
Parabolic Critical Depth
Global Vel Dist= 0 , 0 , 0
Global Log Level= 0
CheckData=True
Encroach Param=-1 ,0,0, 0
Computation Interval=1MIN
Output Interval=1HOUR
Instantaneous Interval=1HOUR
Mapping Interval=1HOUR
Computation Time Step Use Courant=        0
Computation Time Step Use Time Series=    0
Computation Time Step Count To Double=0
Computation Time Step Max Doubling=0
Computation Time Step Max Halving=0
Computation Time Step Residence Courant=0
Run HTab= 0
Run UNet= 0
Run Sediment= 0
Run PostProcess= 0
Run WQNet= 0
Run RASMapper= 0
UNET Theta= 1
UNET Theta Warmup= 1
UNET ZTol= 0.02
UNET ZSATol= 0.02
UNET MxIter= 20
UNET Max Iter WO Improvement= 0
UNET MaxInSteps= 0
UNET DtIC= 0
UNET DtMin= 0
UNET MaxCRTS= 20
UNET WFStab= 2
UNET SFStab= 1
UNET WFX= 1
UNET SFX= 1
UNET Gravity=32.174
UNET 1D Methodology=Finite Difference
UNET DSS MLevel= 4
UNET Pardiso=0
UNET DZMax Abort= 100
UNET Use Existing IB Tables=-1
UNET Froude Reduction=False
UNET Froude Limit= 0.8
UNET Froude Power= 4
UNET D1 Cores= 0
UNET WindReference=Eulerian
UNET WindDragFormulation=Hsu (1988)
UNET D2 Coriolis=0
UNET D2 Cores= 0
UNET D2 Theta= 1
UNET D2 Theta Warmup= 1
UNET D2 Z Tol= 0.01
UNET D2 Volume Tol= 0.01
UNET D2 Max Iterations= 20
UNET D2 Equation= 0
UNET D2 RampUpFraction=0.1
UNET D2 TimeSlices= 1
UNET D2 Turbulence Formulation=None
UNET D2 Eddy Viscosity=0.3
UNET D2 Transverse Eddy Viscosity=0.1
UNET D2 Smagorinsky Mixing=0.05
UNET D2 BCVolumeCheck=0
UNET D2 Cores=0
UNET D2 SolverType=PARDISO (Direct)
UNET D2 Minimum Iterations= 2147483647
UNET D2 Maximum Iterations= 2147483647
UNET D2 Restart Number= 10
UNET D2 Relaxation Coeff=1.3
UNET D2 SOR Precondition Iterations= 10
UNET D2 ILUT Maximum Fill= 8
UNET D2 ILUT Tolerance=1E-08
UNET D1D2 MaxIter= 0
UNET D1D2 ZTol=0.01
UNET D1D2 QTol=0.1
UNET D1D2 MinQTol=1
Write IC File= 0
Write IC File at Fixed DateTime=0
Write IC File at Sim End=0
Echo Input=False
Echo Parameters=False
Echo Output=False
Write Detailed= 0
HDF Write Warmup=0
HDF Write Time Slices=0
HDF Flush=0
HDF Compression= 1
HDF Chunk Size= 1
HDF Spatial Parts= 1
HDF Use Max Rows=0
HDF Fixed Rows= 1
Calibration Method= 0
Calibration Iterations= 20
Calibration Max Change=0.05
Calibration Tolerance=0.2
Calibration Maximum=1.5
Calibration Minimum=0.5
Calibration Optimization Method= 1
WQ AD Non Conservative
WQ ULTIMATE=-1
WQ Max Comp Step=1HOUR
WQ Output Interval=15MIN
WQ Output Selected Increments= 0
WQ Output face flow=0
WQ Output face velocity=0
WQ Output face area=0
WQ Output face dispersion=0
WQ Output cell volume=0
WQ Output cell surface area=0
WQ Output cell continuity=0
WQ Output cumulative cell continuity=0
WQ Output face conc=0
WQ Output face dconc_dx=0
WQ Output face courant=0
WQ Output face peclet=0
WQ Output face adv mass=0
WQ Output face disp mass=0
WQ Output cell mass=0
WQ Output cell source sink temp=0
WQ Output nsm pathways=0
WQ Output nsm derived pathways=0
WQ Create Restart=0
WQ Fixed Restart=0
WQ System Summary=0
WQ Write To DSS=0
Sorting and Armoring Iterations= 10
XS Update Threshold= 0.02
Bed Roughness Predictor= 0
Hydraulics Update Threshold= 0.02
Energy Slope Method= 1
Volume Change Method= 1
Sediment Retention Method= 0
Sediment TS Multiplier= 1
Warm Up Method= 0
XS Weighting Method= 0
Number of US Weighted Cross Sections= 1
Number of DS Weighted Cross Sections= 1
Upstream XS Weight=0
Main XS Weight=1
Downstream XS Weight=0
Number of DS XS's Weighted with US Boundary= 1
Upstream Boundary Weight= 1
Weight of XSs Associated with US Boundary= 0
Number of US XS's Weighted with DS Boundary= 1
Downstream Boundary Weight= 0.5
Weight of XSs Associated with DS Boundary= 0.5
Percentile Method= 0
Sediment Output Level= 3
Mass or Volume Output= 0
Output Increment Type= 1
Profile and TS Output Increment= 1
Transport Output Increment 1
XS Output Flag= 0
XS Output Increment= 10
Read HDF5 Sediment Hotstart= 0
Sediment Hotstart Type= 0
Write Gradation File= 0
Read Gradation Hotstart= 0
Write HDF5 File= 1
Write Binary Output= 1
Write DSS Sediment File= 0
DSS Sediment Output Type= 1
SV Curve= 0
Specific Gage Flag= 0
Subcell Erosion Methods= 0
Subcell Deposition Methods= 0
Advection Scheme= 1
Matrix Solver= 0
Implicit Weighting Factor= 1
Maximum Outer Loop Convergence Iterations= 5
Convergence Maximum Absolute= 0.001
Convergence RMSE= 0.0001
Grain Fractions Max Abs Error= 0.001
Max Subgrid Regions= 1
Max Subgrid Length Scale= 3.402823E+38
Initial Layer Thickness= 3.402823E+38
Min Layer Thickness= 3.402823E+38
Max Layer Thickness= 3.402823E+38
Number of Layers= 5

--- Wheeling Creek.p01 (plan) ---

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Plan Title=Existing
Short Identifier=EX
Geom File=g01
Flow File=f01

--- Wheeling Creek.p02 (plan) ---

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Plan Title=Proposed - Initial Layout
Short Identifier=PROP - Initial
Geom File=g02
Flow File=f01

--- Wheeling Creek.p03 (plan) ---

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Plan Title=Proposed + 2'
Short Identifier=PROP + 2'
Geom File=g03
Flow File=f01

--- Wheeling Creek.p04 (plan) ---

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Plan Title=Proposed + 2' + VA
Short Identifier=PROP + 2' + VA
Geom File=g04
Flow File=f01

--- Wheeling Creek.p05 (plan) ---

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Plan Title=Proposed + VA
Short Identifier=PROP + VA
Geom File=g05
Flow File=f01

--- Wheeling Creek.p06 (plan) ---

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Plan Title=Proposed + No Rail
Short Identifier=PROP + No Rail
Geom File=g06
Flow File=f01

--- Wheeling Creek.p07 (plan) ---

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Plan Title=Proposed + No Rail + VA
Short Identifier=PROP + No Rail + VA
Geom File=g07
Flow File=f01

--- Wheeling Creek.p08 (plan) ---

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Plan Title=Proposed - Culvert
Short Identifier=PROP - Culvert
Geom File=g08
Flow File=f01

--- Wheeling Creek.p09 (plan) ---

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Plan Title=Proposed + 2' + VA + No Rail
Short Identifier=PROP + 2' + VA + No Rail
Geom File=g09
Flow File=f01

--- Wheeling Creek.p10 (plan) ---

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Plan Title=Proposed + 4' + VA + No Rail
Short Identifier=PROP + 4' + VA + No Rail
Geom File=g10
Flow File=f01

--- Wheeling Creek.p11 (plan) ---

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Plan Title=Proposed + 3' + VA + No Rail
Short Identifier=PROP + 3' + VA + No Rail
Geom File=g11
Flow File=f01

--- Wheeling Creek.f01 (steady flow) ---

Flow Title=StreamStats
Program Version=6.20
Number of Profiles= 9
Profile Names=STD,OHW,2-YR,5-YR,10-YR,25-YR,50-YR,100-YR,500-YR
River Rch & RM=Wheeling Creek,Wheeling Creek  ,5744.4
     256     347    2170    3490    4490    5900    7040    8230   11300
River Rch & RM=Wheeling Creek,Wheeling Creek  ,5340.6
     256     347    2170    3490    4490    5900    7040    8230   11300
Boundary for River Rch & Prof#=Wheeling Creek,Wheeling Creek  , 1
Up Type= 0
Dn Type= 3
Dn Slope=0.00337
Boundary for River Rch & Prof#=Wheeling Creek,Wheeling Creek  , 2
Up Type= 0
Dn Type= 3
Dn Slope=0.00337
Boundary for River Rch & Prof#=Wheeling Creek,Wheeling Creek  , 3
Up Type= 0
Dn Type= 3
Dn Slope=0.00337
Boundary for River Rch & Prof#=Wheeling Creek,Wheeling Creek  , 4
Up Type= 0
Dn Type= 3
Dn Slope=0.00337
Boundary for River Rch & Prof#=Wheeling Creek,Wheeling Creek  , 5
Up Type= 0
Dn Type= 3
Dn Slope=0.00337
Boundary for River Rch & Prof#=Wheeling Creek,Wheeling Creek  , 6
Up Type= 0
Dn Type= 3
Dn Slope=0.00337
Boundary for River Rch & Prof#=Wheeling Creek,Wheeling Creek  , 7
Up Type= 0
Dn Type= 3
Dn Slope=0.00337
DSS Import GetInterval= 0
DSS Import GetPeak= 0
DSS Import FillOption= 0

--- Wheeling Creek.f02 (steady flow) ---

Flow Title=StreamStats - Conv (-)
Program Version=6.20
Number of Profiles= 7
Profile Names=2-YR,5-YR,10-YR,25-YR,50-YR,100-YR,500-YR
River Rch & RM=Wheeling Creek,Wheeling Creek  ,5744.4
    2170    3490    4490    5900    7040    8230   11300
River Rch & RM=Wheeling Creek,Wheeling Creek  ,5340.6
    2170    3490    4490    5900    7040    8230   11300
Boundary for River Rch & Prof#=Wheeling Creek,Wheeling Creek  , 1
Up Type= 0
Dn Type= 3
Dn Slope=0.0068
Boundary for River Rch & Prof#=Wheeling Creek,Wheeling Creek  , 2
Up Type= 0
Dn Type= 3
Dn Slope=0.0068
Boundary for River Rch & Prof#=Wheeling Creek,Wheeling Creek  , 3
Up Type= 0
Dn Type= 3
Dn Slope=0.0068
Boundary for River Rch & Prof#=Wheeling Creek,Wheeling Creek  , 4
Up Type= 0
Dn Type= 3
Dn Slope=0.0068
Boundary for River Rch & Prof#=Wheeling Creek,Wheeling Creek  , 5
Up Type= 0
Dn Type= 3
Dn Slope=0.0068
Boundary for River Rch & Prof#=Wheeling Creek,Wheeling Creek  , 6
Up Type= 0
Dn Type= 3
Dn Slope=0.0068
Boundary for River Rch & Prof#=Wheeling Creek,Wheeling Creek  , 7
Up Type= 0
Dn Type= 3
Dn Slope=0.0068
DSS Import GetInterval= 0
DSS Import GetPeak= 0
DSS Import FillOption= 0

--- Wheeling Creek.f03 (steady flow) ---

Flow Title=StreamStats - Conv (+)
Program Version=6.20
Number of Profiles= 7
Profile Names=2-YR,5-YR,10-YR,25-YR,50-YR,100-YR,500-YR
River Rch & RM=Wheeling Creek,Wheeling Creek  ,5744.4
    2170    3490    4490    5900    7040    8230   11300
River Rch & RM=Wheeling Creek,Wheeling Creek  ,5340.6
    2170    3490    4490    5900    7040    8230   11300
Boundary for River Rch & Prof#=Wheeling Creek,Wheeling Creek  , 1
Up Type= 0
Dn Type= 3
Dn Slope=0.0022
Boundary for River Rch & Prof#=Wheeling Creek,Wheeling Creek  , 2
Up Type= 0
Dn Type= 3
Dn Slope=0.0022
Boundary for River Rch & Prof#=Wheeling Creek,Wheeling Creek  , 3
Up Type= 0
Dn Type= 3
Dn Slope=0.0022
Boundary for River Rch & Prof#=Wheeling Creek,Wheeling Creek  , 4
Up Type= 0
Dn Type= 3
Dn Slope=0.0022
Boundary for River Rch & Prof#=Wheeling Creek,Wheeling Creek  , 5
Up Type= 0
Dn Type= 3
Dn Slope=0.0022
Boundary for River Rch & Prof#=Wheeling Creek,Wheeling Creek  , 6
Up Type= 0
Dn Type= 3
Dn Slope=0.0022
Boundary for River Rch & Prof#=Wheeling Creek,Wheeling Creek  , 7
Up Type= 0
Dn Type= 3
Dn Slope=0.0022
DSS Import GetInterval= 0
DSS Import GetPeak= 0
DSS Import FillOption= 0

--- Wheeling Creek.g18 (geometry) ---

Geom Title=TAF
Program Version=6.20

River Reach=Wheeling Creek  ,Wheeling Creek
Reach XY= 30
      187843.167      592120.036      187831.037      592141.166
      187820.903       592161.67      187804.392      592188.119
      187794.757      592206.071      187767.245      592250.426
      187755.653      592268.713      187724.276      592310.512
       187710.27      592332.812      187680.747      592374.745
      187664.489      592395.385      187649.731      592419.316
      187637.671      592440.836      187622.742       592463.46
      187600.199      592504.114      187585.536      592527.352
      187560.971      592562.949      187514.095      592646.272
       187503.89      592666.268      187474.137      592710.181
      187463.236      592728.991      187446.479      592748.427
      187435.575      592768.597      187425.991      592792.896
      187370.327      592906.929      187354.913      592936.541
      187331.635      592986.155      187323.243      593010.475
       187297.82       593078.24      187291.098      593102.498

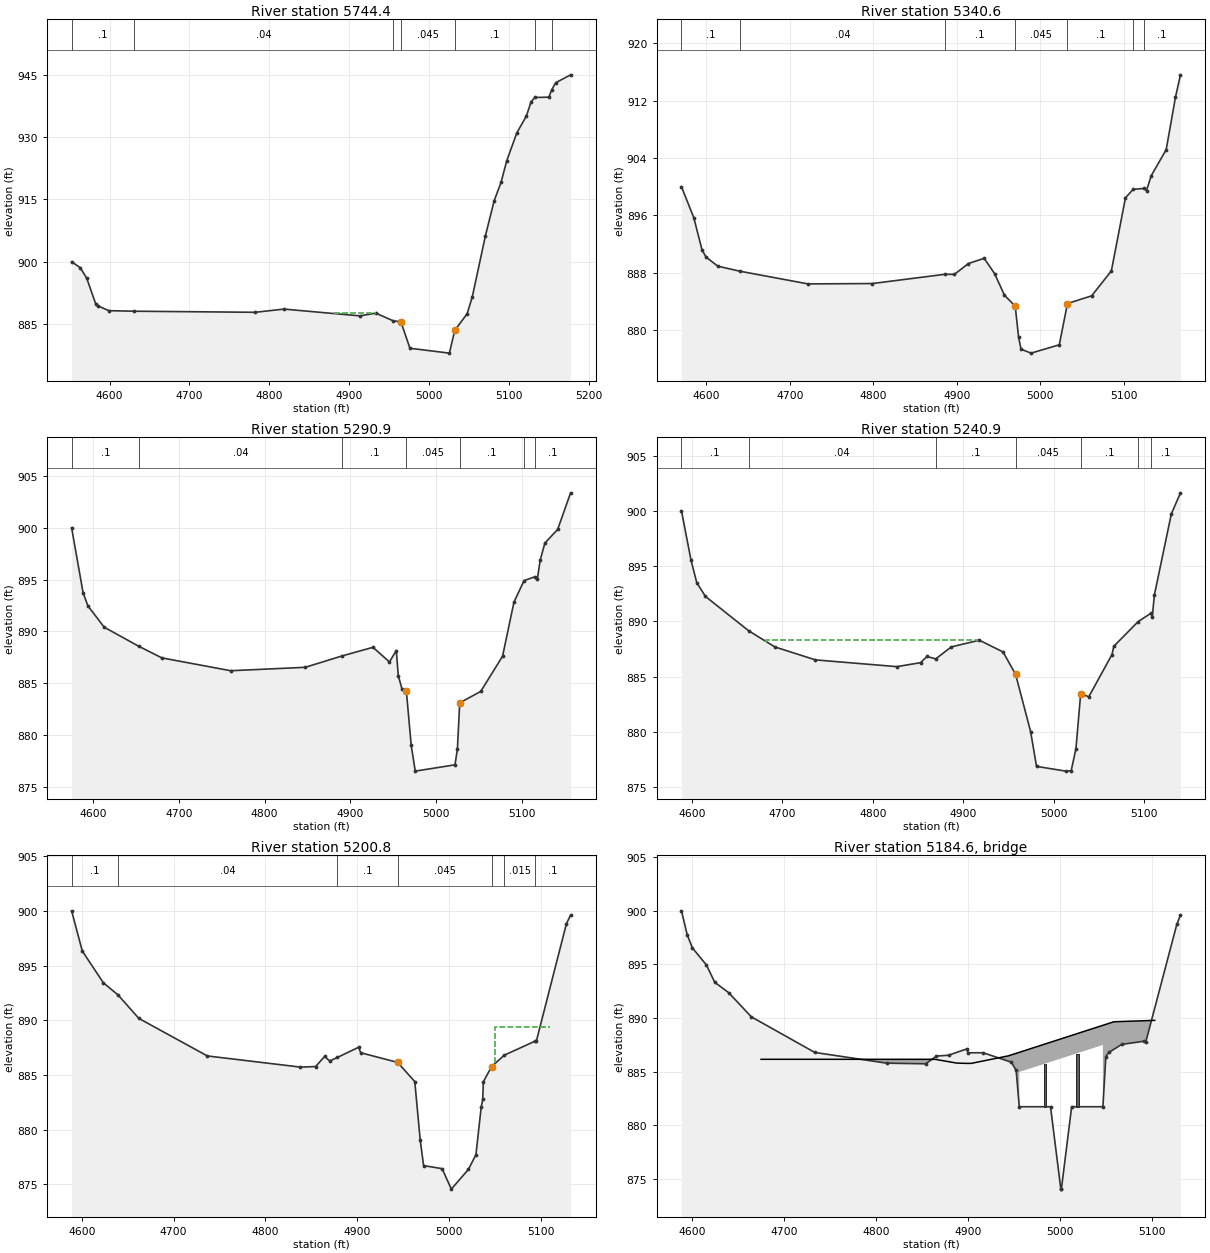
Type RM Length L Ch R = 1 ,5744.4  ,403.8,403.8,403.8
XS GIS Cut Line= 2
      187458.119      591892.067      187996.231      592210.658
#Sta/Elev= 30
  4552.5     900  4563.3  898.58  4571.4  896.05  4582.8  889.81    4585  889.43
  4599.2  888.24  4630.9  888.11  4782.5  887.85  4818.5  888.62  4913.5  886.99
  4933.5  887.64  4955.1  885.81  4964.9  885.54  4976.2   879.2  5025.6  878.03
  5032.3  883.48  5047.8   887.5  5054.2   891.5  5070.8  906.31  5081.7  914.69
  5090.3   919.1  5097.5  924.33  5110.1  931.02    5122  935.04  5127.9  938.45
  5132.5  939.51  5150.2  939.59  5153.7  941.34  5158.7  943.06  5177.4  944.96
#Mann= 7 ,-1,0
  4552.5      .1       0  4630.9     .04       0  4955.1      .1       0
  4964.9    .045       0  5032.3      .1       0  5132.5    .012       0
  5153.7     .04       0
#XS Ineff= 2 ,-1
  4588.6  4818.5  888.62    4882  4933.5  887.64
Permanent Ineff=
       F       F
Bank Sta=4964.9,5032.3
XS Rating Curve= 0 ,0
Exp/Cntr=0.3,0.1

Type RM Length L Ch R = 1 ,5340.6  ,49.8,49.8,49.8
XS GIS Cut Line= 2
      187249.437      592251.215      187773.112      592541.084
#Sta/Elev= 30
  4570.2  899.99    4585  895.66  4594.7  891.23  4599.5  890.19  4613.8  888.91
  4640.2  888.21  4721.8  886.44  4798.7  886.49  4885.9  887.78  4897.2  887.77
    4914  889.28  4932.9  890.01  4945.4  887.87  4957.2  884.87  4970.1  883.33
  4974.1  879.04  4977.1  877.34  4989.1  876.79  5022.9  877.95  5032.7   883.7
  5061.7  884.78  5085.3  888.25  5102.2  898.45  5111.4  899.62    5124  899.75
  5127.4  899.46  5133.1  901.53    5151  905.16  5162.1  912.46  5168.1  915.59
#Mann= 7 ,-1,0
  4570.2      .1       0  4640.2     .04       0  4885.9      .1       0
  4970.1    .045       0  5032.7      .1       0  5111.4    .015       0
    5124      .1       0
#XS Ineff= 2 , 0
       0  4932.9  890.01               0
Permanent Ineff=
       F       F
Bank Sta=4970.1,5032.7
XS Rating Curve= 0 ,0
Exp/Cntr=0.3,0.1

Type RM Length L Ch R = 1 ,5290.9  ,49.9,49.9,49.9
XS GIS Cut Line= 2
      187228.999      592296.785      187739.119      592579.151
#Sta/Elev= 30
  4574.8  900.01  4588.2  893.73  4593.8  892.47  4612.8  890.41  4653.4  888.56
  4680.1  887.45  4760.4  886.21  4847.4  886.54  4890.9  887.65  4926.5  888.47
  4945.7  887.06  4953.7  888.16    4956  885.73  4960.4  884.43  4965.4  884.28
  4971.1  879.01  4975.8  876.52  5022.2  877.13    5025  878.65  5027.7  883.11
  5052.2  884.21  5077.7  887.61    5091  892.83  5102.8  894.91  5115.9  895.29
  5118.3  895.06  5121.7  896.91  5127.1  898.53    5142  899.85  5157.1  903.38
#Mann= 7 ,-1,0
  4574.8      .1       0  4653.4     .04       0  4890.9      .1       0
  4965.4    .045       0  5027.7      .1       0  5102.8    .015       0
  5115.9      .1       0
#XS Ineff= 2 ,-1
    4654  4926.5  888.47  4926.5  4953.7  888.16
Permanent Ineff=
       F       F
Bank Sta=4965.4,5027.7
XS Rating Curve= 0 ,0
Exp/Cntr=0.3,0.1

Type RM Length L Ch R = 1 ,5240.9  ,40.1,40.1,40.1
XS GIS Cut Line= 2
      187213.715      592345.207       187699.34      592614.014
#Sta/Elev= 30
  4588.5     900  4599.1  895.52  4605.4   893.5    4615  892.26  4662.8  889.15
  4691.8  887.69  4736.6  886.52  4826.6  885.91  4852.7  886.27  4859.9  886.83
  4869.5  886.61  4886.6  887.69  4917.7   888.3  4943.9  887.24  4957.8  885.21
  4974.4  880.03  4980.9  876.89  5013.2  876.46  5019.2  876.49  5024.5   878.5
  5029.7  883.45  5038.7  883.19  5064.3     887  5066.3  887.75  5093.2  889.98
    5107  890.72  5108.9  890.43  5111.1  892.36  5129.9  899.72    5140  901.63
#Mann= 7 ,-1,0
  4588.5      .1       0  4662.8     .04       0  4869.5      .1       0
  4957.8    .045       0  5029.7      .1       0  5093.2    .015       0
    5107      .1       0
#XS Ineff= 2 ,-1
    4682  4916.5  888.31  4916.5  4933.2  887.49
Permanent Ineff=
       F       F
Bank Sta=4957.8,5029.7
XS Rating Curve= 0 ,0
Exp/Cntr=0.5,0.3

Type RM Length L Ch R = 1 ,5200.8  ,33,33,33
XS GIS Cut Line= 2
      187192.751      592379.322       187668.22      592642.508
#Sta/Elev= 30
    4589     900  4600.6  896.33  4623.6  893.42  4639.5  892.32  4662.2  890.17
  4736.8  886.74  4838.2  885.72  4854.7  885.77  4864.5  886.69  4870.1  886.28
  4878.3   886.6  4901.5  887.53  4903.9  887.03    4944  886.15  4962.7   884.4
  4968.6  879.08  4972.3  876.72  4992.5  876.44  5002.5  874.57  5021.2  876.38
  5029.3  877.72  5035.1   882.1  5036.7  882.76  5037.4  884.38  5046.3  885.76
  5060.2  886.81  5093.4  888.08  5095.1  888.09  5127.9  898.84  5132.4  899.61
#Mann= 7 ,-1,0
    4589      .1       0  4639.5     .04       0  4878.3      .1       0
    4944    .045       0  5046.3      .1       0  5060.2    .015       0
  5093.4      .1       0
#XS Ineff= 3 ,-1
    4711  4901.5  887.53  4901.5    4944     886  5050.2    5110   889.4
Permanent Ineff=
       F       T       T
Bank Sta=4944,5046.3
XS Rating Curve= 0 ,0
Exp/Cntr=0.5,0.3

Type RM Length L Ch R = 3 ,5184.6  ,,,
Bridge Culvert--1,0,-1,-1, 0
Deck Dist Width WeirC Skew NumUp NumDn MinLoCord MaxHiCord MaxSubmerge Is_Ogee
6.6,20,2.6,0, 24, 24, , , 0.98, 0, 2,2,,
    4675    4864    4865  4887.8    4898  4898.3  4899.1  4899.8  4900.4    4901
  4901.4    4902  4902.2  4902.6  4902.9  4903.4  4903.7    4944    4956    4956
    5047    5047    5059  5103.4
  886.16  886.16  886.15  885.81  885.78  885.78  885.78  885.78  885.78  885.78
  885.78  885.78  885.78  885.78  885.78  885.78  885.78  886.48  886.81  886.81
  889.33  889.33  889.66  889.79
                                                                                
                                                                          884.98
   887.5
    4675    4864    4865  4887.8    4898  4898.3  4899.1  4899.8  4900.4    4901
  4901.4    4902  4902.2  4902.6  4902.9  4903.4  4903.7    4944    4956    4956
    5047    5047    5059  5103.4
  886.16  886.16  886.15  885.81  885.78  885.78  885.78  885.78  885.78  885.78
  885.78  885.78  885.78  885.78  885.78  885.78  885.78  886.48  886.81  886.81
  889.33  889.33  889.66  889.79
                                                                                
                                                                          884.98
   887.5
Pier Skew, UpSta & Num, DnSta & Num=  ,4984, 4 ,4984, 4 , 3 , 3 , 0 ,,
       2       2       3       3
     875   883.7   883.7   885.7
       2       2       3       3
     875   883.7   883.7   885.7
Pier Skew, UpSta & Num, DnSta & Num=  ,5019, 4 ,5019, 4 , 3 , 3 , 0 ,,
       2       2       3       3
     875  884.66  884.66  886.66
       2       2       3       3
     875  884.66  884.66  886.66
Abutment Skew #Up #Dn= , 4 , 4
    4956    4957    4957  4970.1
  884.98  884.98  881.95  875.38
    4956    4957    4957  4970.1
  884.98  884.98  881.95  875.38
Abutment Skew #Up #Dn= , 4 , 4
    5036    5046    5046    5047
   878.4   883.4   887.5   887.5
    5036    5046    5046    5047
   878.4   883.4   887.5   887.5
BR Coef=-1 , 1 , 0 ,1.05, 0 ,,,0.8,0,1.2,0,
WSPro=,,,, 1 ,,,, 0 ,,,, 0 ,,,,-1 ,-1 ,-1 , 0 , 0 , 0 , 0 , 0
BR U #Sta/Elev= 30
  4588.4     900  4594.6  897.78  4600.2  896.55  4615.6  894.95  4624.6  893.34
  4639.8  892.37  4664.4  890.12  4733.5   886.8  4811.7   885.8  4854.2  885.74
  4865.9  886.46    4879  886.54  4898.6  887.12  4900.4  886.77  4916.7  886.77
  4947.4  885.89  4952.6  885.12    4956  881.74    4990  881.74 5001.16   874.1
  5001.8  874.06    5013  881.74    5047  881.74  5050.2  886.42  5053.7  886.81
  5067.5  887.55  5091.4  887.84  5093.6  887.75  5127.4  898.73  5131.4  899.61
BR U #Mann= 7
  4588.4      .1  4639.8     .04    4879      .1    4956    .045    5047      .1
  5053.7    .015  5091.4      .1
BR U Banks=4952.6,5050.2
BR D #Sta/Elev= 30
  4593.1     900  4597.3  898.71  4602.5  897.71  4607.5  897.18  4610.2  896.35
  4617.8  894.78  4628.7  893.29  4634.6  892.82  4658.1  890.48    4672  889.56
  4734.9  886.92  4786.4  886.14  4803.8  885.63    4847     886  4858.9  885.54
  4890.9   885.5    4925  884.99  4948.9  884.25    4959  881.74    4987  881.74
 4997.49  876.81  5005.7  876.91    5016  881.74    5044  881.74  5049.5  885.58
  5081.7  886.22    5084  886.55  5114.6  895.04  5121.7  897.35  5132.5  899.88
BR D #Mann= 6
  4593.1      .1  4634.6     .04  4890.9     .02  4948.9      .1    4959    .045
    5044      .1
BR D Banks=4948.9,5049.5
BC Design=,, 0 ,, 0 ,,,,,,
BC Use User HTab Curves=0
BC User HTab FreeFlow(D)= 0

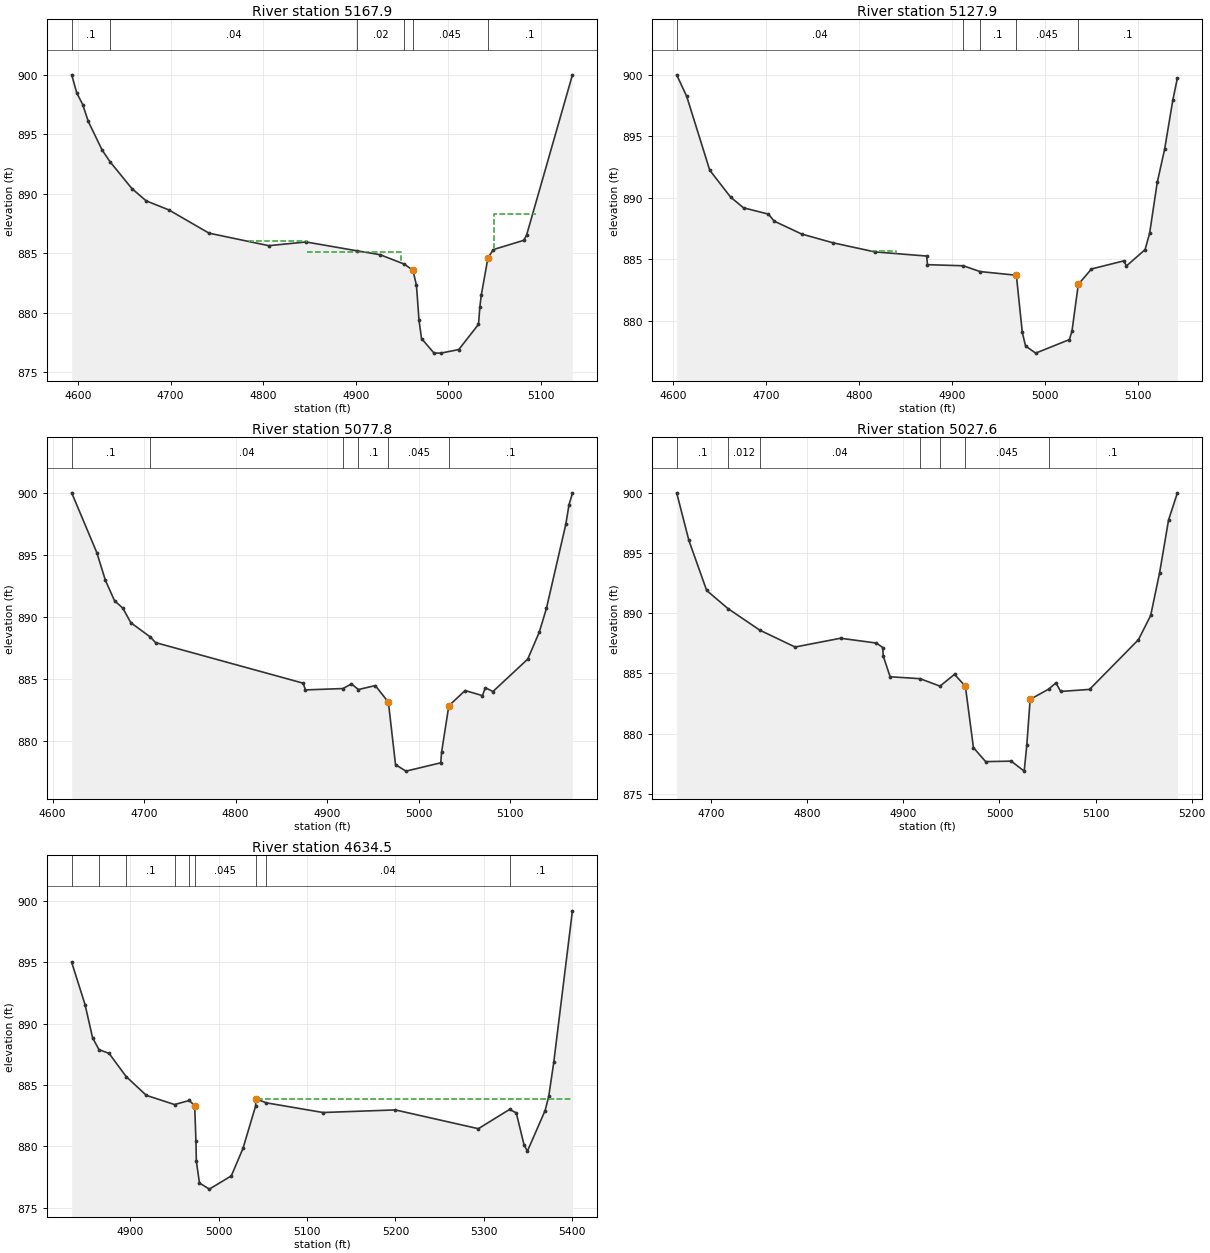
Type RM Length L Ch R = 1 ,5167.9  ,40,40,40
XS GIS Cut Line= 2
      187180.212      592410.067      187653.156      592671.855
#Sta/Elev= 30
  4593.2  900.01  4598.7  898.48  4605.1  897.51  4611.1  896.09    4626  893.69
  4634.6   892.7  4658.2  890.44  4673.6  889.41    4698  888.65  4741.5  886.69
  4805.9  885.64  4846.3  885.95  4901.7   885.2  4926.1  884.88  4952.2  884.09
  4961.6  883.57  4965.4  882.31  4968.2  879.35  4970.9  877.83  4984.3  876.61
  4991.7   876.6  5011.1   876.9  5032.4  879.02  5033.9   880.5  5035.4  881.48
  5042.6  884.61  5048.4  885.31  5081.3  886.09  5084.3  886.52  5133.8     900
#Mann= 6 ,-1,0
  4593.2      .1       0  4634.6     .04       0  4901.7     .02       0
  4952.2      .1       0  4961.6    .045       0  5042.6      .1       0
#XS Ineff= 3 ,-1
    4785    4847     886    4847  4948.9  885.13  5049.5    5095  888.27
Permanent Ineff=
       F       T       T
Bank Sta=4961.6,5042.6
XS Rating Curve= 0 ,0
Exp/Cntr=0.5,0.3

Type RM Length L Ch R = 1 ,5127.9  ,50.1,50.1,50.1
XS GIS Cut Line= 4
      187169.759         592450.      187598.308      592687.214
      187598.308      592687.214      187647.027      592699.763
#Sta/Elev= 30
  4603.7  899.99  4614.5  898.24  4639.3  892.24  4661.8  890.05  4675.7  889.18
  4702.5  888.67  4708.7   888.1  4738.3  887.05  4771.9  886.34  4816.9   885.6
  4872.9  885.26  4873.8  884.56  4912.4  884.47  4930.4     884  4969.5   883.7
  4975.9  879.05  4979.4  877.95  4990.3  877.37  5026.6  878.47  5029.4  879.16
  5036.2  882.96  5050.4  884.21  5085.2  884.87  5088.1  884.46  5108.1  885.78
    5113  887.11  5121.2  891.24  5129.2  893.96    5138  897.94  5142.9  899.73
#Mann= 5 ,-1,0
  4603.7     .04       0  4912.4    .015       0  4930.4      .1       0
  4969.5    .045       0  5036.2      .1       0
#XS Ineff= 2 ,-1
    4690  4702.5  888.67    4813  4839.5  885.66
Permanent Ineff=
       F       F
Bank Sta=4969.5,5036.2
XS Rating Curve= 0 ,0
Exp/Cntr=0.3,0.1

Type RM Length L Ch R = 1 ,5077.8  ,50.2,50.2,50.2
XS GIS Cut Line= 6
      187153.889      592546.215      187213.874      592531.567
      187213.874      592531.567      187577.626      592732.914
      187577.626      592732.914        187646.9      592738.452
#Sta/Elev= 30
  4620.9     900  4648.3  895.19  4657.7  892.96  4667.7  891.31  4676.7  890.72
  4685.5  889.54  4706.6   888.4  4712.5  887.94  4873.8  884.67  4876.1  884.13
  4917.2  884.24  4926.4  884.61  4934.1  884.16  4952.5  884.48  4966.8  883.14
  4974.6  878.11    4986  877.59    5024  878.26  5024.9  879.11  5032.8  882.85
  5050.6  884.08  5069.5  883.67  5072.7  884.31    5081     884    5119  886.61
  5131.6  888.78  5139.4  890.69  5160.6  897.47  5164.1  899.05  5167.8  899.95
#Mann= 6 ,-1,0
  4620.9      .1       0  4706.6     .04       0  4917.2    .015       0
  4934.1      .1       0  4966.8    .045       0  5032.8      .1       0
Bank Sta=4966.8,5032.8
XS Rating Curve= 0 ,0
Exp/Cntr=0.3,0.1

Type RM Length L Ch R = 1 ,5027.6  ,393.1,393.1,393.1
XS GIS Cut Line= 6
      187163.172      592587.251      187222.868      592593.695
      187222.868      592593.695      187602.271      592803.705
      187602.271      592803.705       187628.64      592811.271
#Sta/Elev= 30
  4664.1     900  4676.8  896.05  4695.3  891.89  4717.4  890.39  4750.4   888.6
  4787.3  887.19  4834.6  887.92  4871.9  887.52  4878.5  887.15  4879.1  886.43
  4886.2  884.72  4917.3  884.56  4938.1  883.94  4953.2  884.92  4964.5  883.93
  4972.9  878.83  4985.6  877.67  5012.2  877.71  5025.7  876.88  5028.4  879.03
  5031.9  882.84  5051.3   883.7  5058.7  884.21  5063.7   883.5  5093.7  883.67
  5144.6   887.8  5157.3  889.81  5166.6  893.36  5175.9  897.74  5185.1  899.99
#Mann= 7 ,-1,0
  4664.1      .1       0  4717.4    .012       0  4750.4     .04       0
  4917.3    .015       0  4938.1      .1       0  4964.5    .045       0
  5051.3      .1       0
#XS Ineff= 3 ,-1
    4778  4871.9  887.52  4871.9  4953.2  884.92  5058.7    5101  884.21
Permanent Ineff=
       F       F       F
Bank Sta=4964.5,5031.9
XS Rating Curve= 0 ,0
Exp/Cntr=0.3,0.1

Type RM Length L Ch R = 1 ,4634.5  ,,,
XS GIS Cut Line= 6
        187138.1      593034.228      187157.386      593035.693
      187157.386      593035.693      187627.521      593189.397
      187627.521      593189.397      187669.117      593155.767
#Sta/Elev= 30
  4833.8     895  4848.9  891.55  4857.4  888.85  4864.6  887.88  4876.1  887.57
  4895.4  885.68  4918.2  884.15  4950.1   883.4  4966.8  883.73  4972.9   883.3
  4974.3  880.45  4974.8  878.76  4978.3     877  4989.5   876.5  5014.3  877.58
  5027.5  879.82  5041.8  883.28  5042.1  883.87  5053.8  883.54    5118  882.75
  5199.8  882.96  5293.7  881.43    5329     883  5336.6  882.72  5345.4  880.11
  5349.2   879.6  5369.2  882.91  5373.3  884.06    5379  886.84  5400.1   899.2
#Mann= 9 ,-1,0
  4833.8      .1       0  4864.6     .04       0  4895.4      .1       0
  4950.1    .012       0  4966.8      .1       0  4972.9    .045       0
  5042.1      .1       0  5053.8     .04       0    5329      .1       0
#XS Ineff= 2 , 0
       0                  5043.2       0  883.89
Permanent Ineff=
       F       F
Bank Sta=4972.9,5042.1
XS Rating Curve= 0 ,0
Exp/Cntr=0.3,0.1
LCMann Table=0

Chan Stop Cuts=-1
Use User Specified Reach Order=0
Composite Channel Slope=5

--- Wheeling Creek.g01 (geometry) ---

Geom Title=Existing
Program Version=6.20

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
River Reach=Wheeling Creek  ,Wheeling Creek

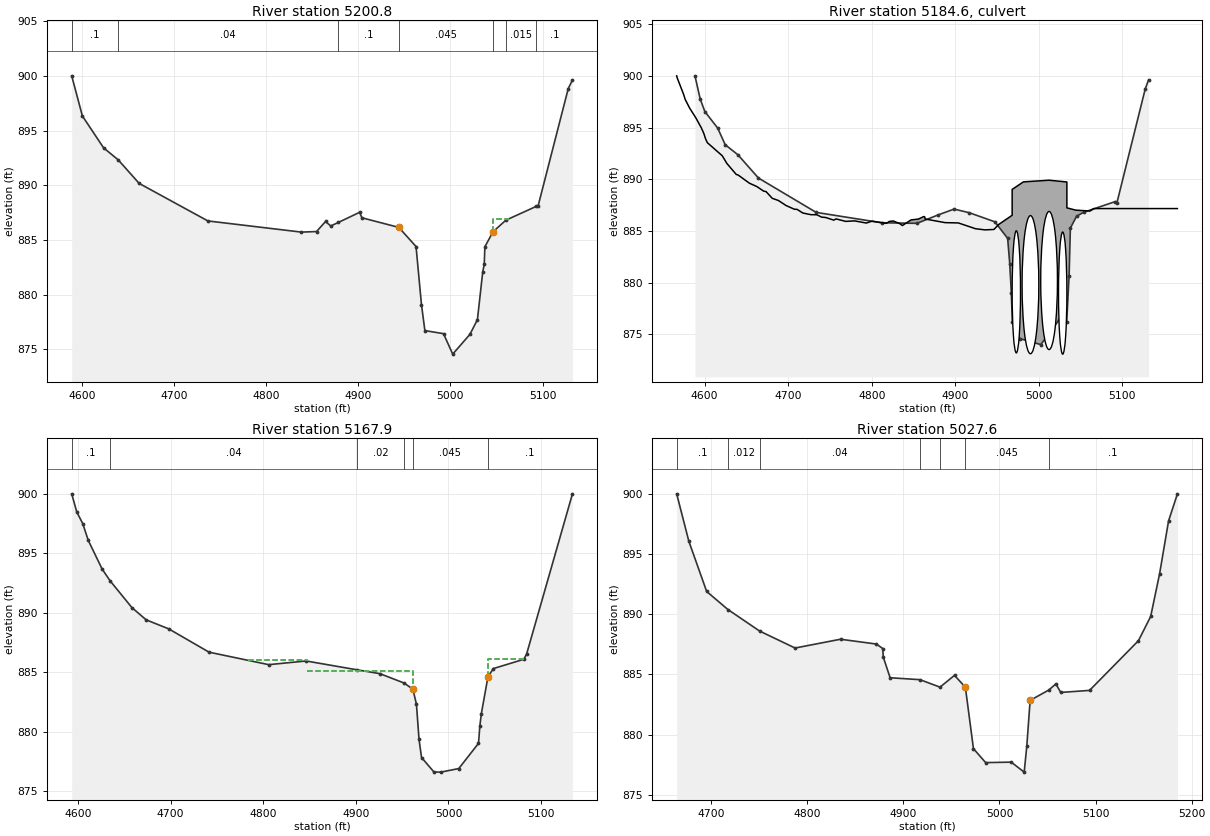
Type RM Length L Ch R = 1 ,5200.8  ,33,33,33
XS GIS Cut Line= 2
      187192.751      592379.322       187668.22      592642.508
#Sta/Elev= 30
    4589     900  4600.6  896.33  4623.6  893.42  4639.5  892.32  4662.2  890.17
  4736.8  886.74  4838.2  885.72  4854.7  885.77  4864.5  886.69  4870.1  886.28
  4878.3   886.6  4901.5  887.53  4903.9  887.03    4944  886.15  4962.7   884.4
  4968.6  879.08  4972.3  876.72  4992.5  876.44  5002.5  874.57  5021.2  876.38
  5029.3  877.72  5035.1   882.1  5036.7  882.76  5037.4  884.38  5046.3  885.76
  5060.2  886.81  5093.4  888.08  5095.1  888.09  5127.9  898.84  5132.4  899.61
#Mann= 7 ,-1,0
    4589      .1       0  4639.5     .04       0  4878.3      .1       0
    4944    .045       0  5046.3      .1       0  5060.2    .015       0
  5093.4      .1       0
#XS Ineff= 3 ,-1
    4711  4901.5  887.53  4901.5    4944  885.58  5046.3    5064  886.94
Permanent Ineff=
       F       T       T
Bank Sta=4944,5046.3
XS Rating Curve= 0 ,0
Exp/Cntr=0.5,0.3

Type RM Length L Ch R = 2 ,5184.6  ,,,
Bridge Culvert--1,0,-1,-1, 0
Deck Dist Width WeirC Skew NumUp NumDn MinLoCord MaxHiCord MaxSubmerge Is_Ogee
9.8,13.2,2.6,0, 60, 60, , , 0.98, 0, 2,2,,
  4566.5  4567.1  4574.8  4576.7  4582.1  4589.5  4595.9    4599  4601.1  4603.2
  4621.1  4626.6  4637.8  4640.1  4653.6  4662.4  4670.7  4673.5  4680.9  4688.3
  4697.3  4707.2  4710.7  4717.5  4727.1  4734.3  4740.1  4744.7  4754.6  4757.3
  4768.8  4779.5  4793.5  4800.3  4817.5  4821.2  4825.9  4833.8  4836.7    4847
  4856.1  4862.3  4863.5    4864  4887.8  4903.7  4924.3  4935.5  4946.3  4952.1
  4968.1  4968.1  4981.6  5012.3  5033.6  5033.6  5044.1  5061.3  5065.9  5165.9
     900  899.81  898.21  897.72  896.87  895.93  894.99  894.43  893.91  893.54
  892.27  891.53  890.47  890.41  889.62   889.3  888.85  888.81  888.16  887.95
  887.47  887.11  887.09  886.74  886.58  886.57  886.34  886.31  886.05  886.17
  885.93  885.98  885.77  885.95  885.74  885.93  885.97   885.7  885.53  886.07
  886.16   886.4  886.36  886.16  885.81  885.78  885.22  885.11  885.15  885.64
  886.52  889.02  889.75  889.91  889.74  887.24  887.02  886.93  887.17  887.17
                                                                                
                                                                                
                                                                                
                                                                                
                                                                                
                                                                                
  4566.5  4567.1  4574.8  4576.7  4582.1  4589.5  4595.9    4599  4601.1  4603.2
  4621.1  4626.6  4637.8  4640.1  4653.6  4662.4  4670.7  4673.5  4680.9  4688.3
  4697.3  4707.2  4710.7  4717.5  4727.1  4734.3  4740.1  4744.7  4754.6  4757.3
  4768.8  4779.5  4793.5  4800.3  4817.5  4821.2  4825.9  4833.8  4836.7    4847
  4856.1  4862.3  4863.5    4864  4887.8  4903.7  4924.3  4935.5  4946.3  4952.1
  4968.1  4968.1  4981.6  5012.3  5033.6  5033.6  5044.1  5061.3  5065.9  5165.9
     900  899.81  898.21  897.72  896.87  895.93  894.99  894.43  893.91  893.54
  892.27  891.53  890.47  890.41  889.62   889.3  888.85  888.81  888.16  887.95
  887.47  887.11  887.09  886.74  886.58  886.57  886.34  886.31  886.05  886.17
  885.93  885.98  885.77  885.95  885.74  885.93  885.97   885.7  885.53  886.07
  886.16   886.4  886.36  886.16  885.81  885.78  885.22  885.11  885.15  885.64
  886.52  889.02  889.75  889.91  889.74  887.24  887.02  886.93  887.17  887.17
                                                                                
                                                                                
                                                                                
                                                                                
                                                                                
                                                                                
BR Coef=-1 , 0 , 0 ,, 0 ,,,0.8,-1,,0,
WSPro=,,,, 1 ,,,, 0 ,,,, 0 ,,,,-1 ,-1 ,-1 , 0 , 0 , 0 , 0 , 0
Culvert=5,11.8,10,26.7,0.024,0.7,1,41,2,873.22,4973.1,873.92,4973.7,Culvert #1  , 0 ,3.3
  4973.1  4973.7
BC Culvert Barrel=1,Barrel #1,0
Culvert Bottom n=0.045
Culvert Bottom Depth=1
Culvert Depth Blocked=1
Culvert=5,13.35,20,26.7,0.024,0.7,1,41,2,873.14,4990,873.43,4990.9,Culvert #2  , 0 ,3.3
    4990  4990.9
BC Culvert Barrel=1,Barrel #1,0
Culvert Bottom n=0.045
Culvert Bottom Depth=1
Culvert Depth Blocked=1
Culvert=5,13.35,20,26.7,0.024,0.7,1,41,2,873.54,5012.3,873.72,5013.6,Culvert #3  , 0 ,3.3
  5012.3  5013.6
BC Culvert Barrel=1,Barrel #1,0
Culvert Bottom n=0.045
Culvert Bottom Depth=1
Culvert Depth Blocked=1
Culvert=5,11.8,10,26.7,0.024,0.7,1,41,2,873.1,5028.6,873.2,5029.6,Culvert #4  , 0 ,3.3
  5028.6  5029.6
BC Culvert Barrel=1,Barrel #1,0
Culvert Bottom n=0.045
Culvert Bottom Depth=1
Culvert Depth Blocked=1
BR U #Sta/Elev= 30
  4588.4     900  4594.6  897.78  4600.2  896.55  4615.6  894.95  4624.6  893.34
  4639.8  892.37  4664.4  890.12  4733.5   886.8  4811.7   885.8  4854.2  885.74
    4879  886.54  4898.6  887.12  4916.7  886.77  4947.4  885.89  4962.7  884.29
  4965.2  881.85  4967.1  879.04 4968.33   876.2  4976.9  874.61  5002.4  874.02
    5024  876.38 5033.37   876.2  5036.3   880.7  5037.8  885.28  5045.2  886.42
  5053.7  886.81  5091.4  887.84  5093.6  887.75  5127.4  898.73  5131.4  899.61
BR U #Mann= 7
  4588.4      .1  4639.8     .04    4879      .1  4962.7    .045  5037.8      .1
  5053.7    .015  5091.4      .1
BR U Banks=4962.7,5037.8
BR D #Sta/Elev= 30
  4593.1     900  4597.3  898.71  4607.5  897.18  4617.8  894.78  4634.6  892.82
  4658.1  890.48    4672  889.56  4734.9  886.92  4803.8  885.63    4847     886
  4858.9  885.54  4890.9   885.5  4953.9  884.25  4962.4  883.89  4965.9  881.56
  4968.2  878.96  4970.5  877.74  4981.4  877.02  4998.6  876.71  5012.1  876.83
  5030.4  878.03  5032.9  879.08  5034.6  880.51  5039.4   882.2  5042.6  885.15
  5081.7  886.22    5084  886.55  5114.6  895.04  5121.7  897.35  5132.5  899.88
BR D #Mann= 6
  4593.1      .1  4634.6     .04  4890.9     .02  4953.9      .1  4962.4    .045
  5042.6      .1
BR D Banks=4962.4,5042.6
BC Design=,, 0 ,, 0 ,,,,,,
BC Use User HTab Curves=0
BC User HTab FreeFlow(D)= 0

Type RM Length L Ch R = 1 ,5167.9  ,40,40,40
XS GIS Cut Line= 2
      187180.212      592410.067      187653.156      592671.855
#Sta/Elev= 30
  4593.2  900.01  4598.7  898.48  4605.1  897.51  4611.1  896.09    4626  893.69
  4634.6   892.7  4658.2  890.44  4673.6  889.41    4698  888.65  4741.5  886.69
  4805.9  885.64  4846.3  885.95  4901.7   885.2  4926.1  884.88  4952.2  884.09
  4961.6  883.57  4965.4  882.31  4968.2  879.35  4970.9  877.83  4984.3  876.61
  4991.7   876.6  5011.1   876.9  5032.4  879.02  5033.9   880.5  5035.4  881.48
  5042.6  884.61  5048.4  885.31  5081.3  886.09  5084.3  886.52  5133.8     900
#Mann= 6 ,-1,0
  4593.2      .1       0  4634.6     .04       0  4901.7     .02       0
  4952.2      .1       0  4961.6    .045       0  5042.6      .1       0
#XS Ineff= 3 ,-1
    4785    4847     886    4847  4961.6   885.1  5042.6    5083  886.12
Permanent Ineff=
       F       T       T
Bank Sta=4961.6,5042.6
XS Rating Curve= 0 ,0
Exp/Cntr=0.5,0.3

Type RM Length L Ch R = 1 ,5027.6  ,393.1,393.1,393.1
XS GIS Cut Line= 6
      187163.172      592587.251      187222.868      592593.695
      187222.868      592593.695      187602.271      592803.705
      187602.271      592803.705       187628.64      592811.271
#Sta/Elev= 30
  4664.1     900  4676.8  896.05  4695.3  891.89  4717.4  890.39  4750.4   888.6
  4787.3  887.19  4834.6  887.92  4871.9  887.52  4878.5  887.15  4879.1  886.43
  4886.2  884.72  4917.3  884.56  4938.1  883.94  4953.2  884.92  4964.5  883.93
  4972.9  878.83  4985.6  877.67  5012.2  877.71  5025.7  876.88  5028.4  879.03
  5031.9  882.84  5051.3   883.7  5058.7  884.21  5063.7   883.5  5093.7  883.67
  5144.6   887.8  5157.3  889.81  5166.6  893.36  5175.9  897.74  5185.1  899.99
#Mann= 7 ,-1,0
  4664.1      .1       0  4717.4    .012       0  4750.4     .04       0
  4917.3    .015       0  4938.1      .1       0  4964.5    .045       0
  5051.3      .1       0
#XS Ineff= 2 ,-1
    4778  4871.9  887.52  5058.7    5101  884.21
Permanent Ineff=
       F       F
Bank Sta=4964.5,5031.9
XS Rating Curve= 0 ,0
Exp/Cntr=0.3,0.1

--- Wheeling Creek.g02 (geometry) ---

Geom Title=Proposed - Initial
Program Version=6.20

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
River Reach=Wheeling Creek  ,Wheeling Creek