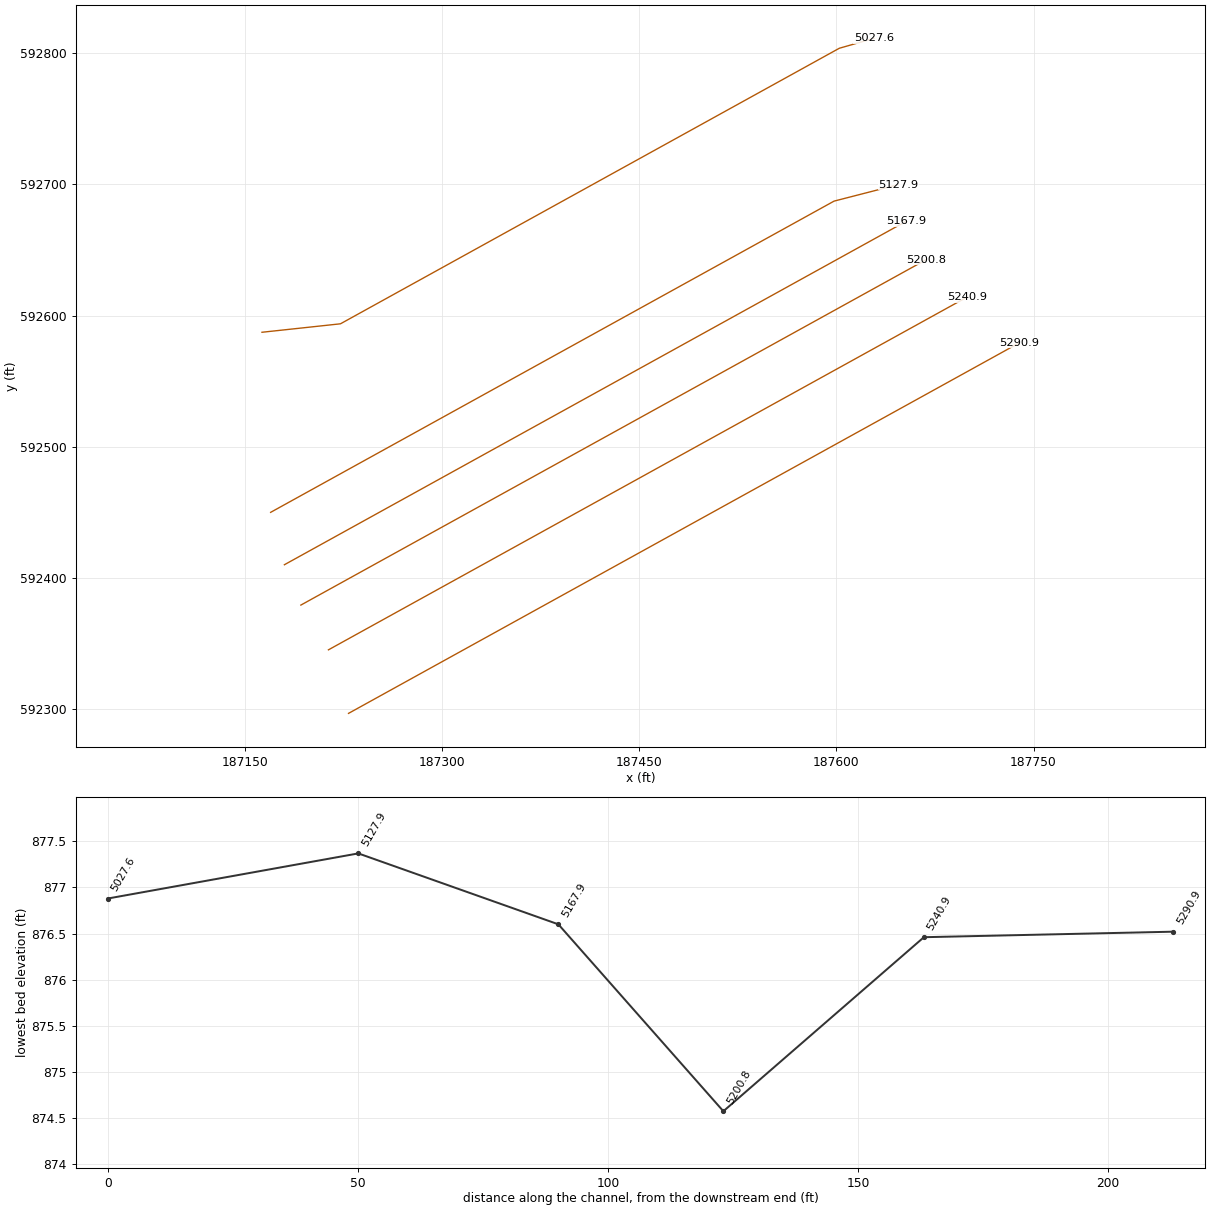
HEC-RAS study Wheeling Creek.prj: 119483_BEL_TR428-0.30 WHEELING CREEK

--- Wheeling Creek.g02 (geometry) --- (continued)

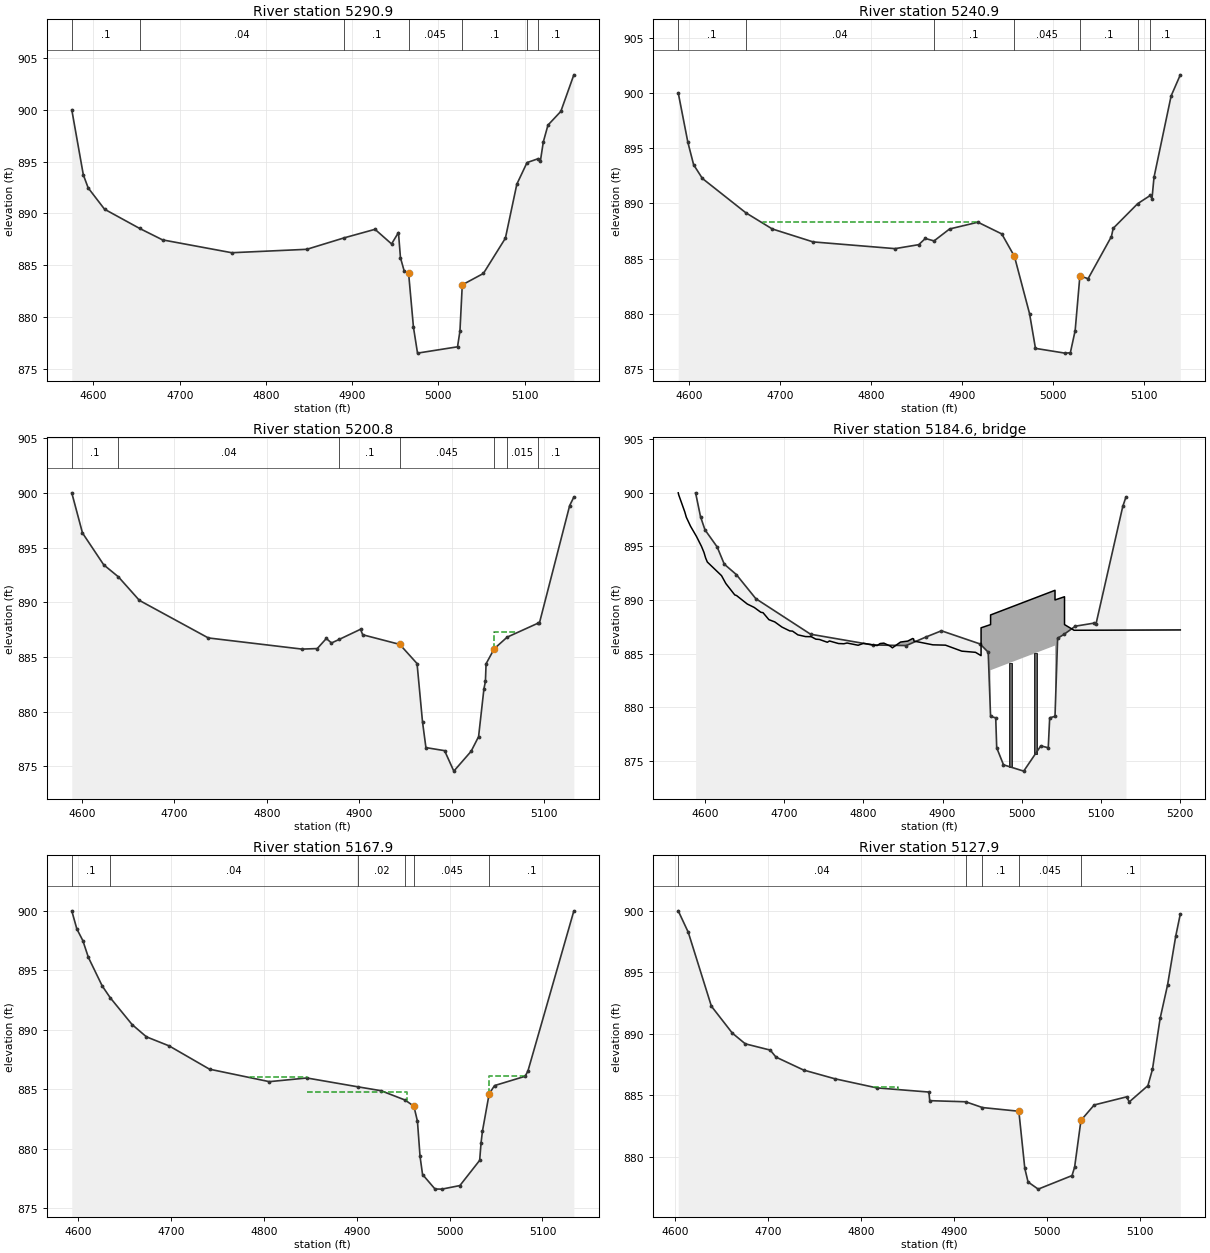
Type RM Length L Ch R = 1 ,5290.9  ,49.9,49.9,49.9
XS GIS Cut Line= 2
      187228.999      592296.785      187739.119      592579.151
#Sta/Elev= 30
  4574.8  900.01  4588.2  893.73  4593.8  892.47  4612.8  890.41  4653.4  888.56
  4680.1  887.45  4760.4  886.21  4847.4  886.54  4890.9  887.65  4926.5  888.47
  4945.7  887.06  4953.7  888.16    4956  885.73  4960.4  884.43  4965.4  884.28
  4971.1  879.01  4975.8  876.52  5022.2  877.13    5025  878.65  5027.7  883.11
  5052.2  884.21  5077.7  887.61    5091  892.83  5102.8  894.91  5115.9  895.29
  5118.3  895.06  5121.7  896.91  5127.1  898.53    5142  899.85  5157.1  903.38
#Mann= 7 ,-1,0
  4574.8      .1       0  4653.4     .04       0  4890.9      .1       0
  4965.4    .045       0  5027.7      .1       0  5102.8    .015       0
  5115.9      .1       0
#XS Ineff= 2 ,-1
    4654  4926.5  888.47  4926.5  4953.7  888.16
Permanent Ineff=
       T       F
Bank Sta=4965.4,5027.7
XS Rating Curve= 0 ,0
Exp/Cntr=0.3,0.1

Type RM Length L Ch R = 1 ,5240.9  ,40.1,40.1,40.1
XS GIS Cut Line= 2
      187213.715      592345.207       187699.34      592614.014
#Sta/Elev= 30
  4588.5     900  4599.1  895.52  4605.4   893.5    4615  892.26  4662.8  889.15
  4691.8  887.69  4736.6  886.52  4826.6  885.91  4852.7  886.27  4859.9  886.83
  4869.5  886.61  4886.6  887.69  4917.7   888.3  4943.9  887.24  4957.8  885.21
  4974.4  880.03  4980.9  876.89  5013.2  876.46  5019.2  876.49  5024.5   878.5
  5029.7  883.45  5038.7  883.19  5064.3     887  5066.3  887.75  5093.2  889.98
    5107  890.72  5108.9  890.43  5111.1  892.36  5129.9  899.72    5140  901.63
#Mann= 7 ,-1,0
  4588.5      .1       0  4662.8     .04       0  4869.5      .1       0
  4957.8    .045       0  5029.7      .1       0  5093.2    .015       0
    5107      .1       0
#XS Ineff= 2 ,-1
    4682  4916.5  888.31  4916.5  4933.2  887.49
Permanent Ineff=
       T       T
Bank Sta=4957.8,5029.7
XS Rating Curve= 0 ,0
Exp/Cntr=0.5,0.3

Type RM Length L Ch R = 1 ,5200.8  ,33,33,33
XS GIS Cut Line= 2
      187192.751      592379.322       187668.22      592642.508
#Sta/Elev= 30
    4589     900  4600.6  896.33  4623.6  893.42  4639.5  892.32  4662.2  890.17
  4736.8  886.74  4838.2  885.72  4854.7  885.77  4864.5  886.69  4870.1  886.28
  4878.3   886.6  4901.5  887.53  4903.9  887.03    4944  886.15  4962.7   884.4
  4968.6  879.08  4972.3  876.72  4992.5  876.44  5002.5  874.57  5021.2  876.38
  5029.3  877.72  5035.1   882.1  5036.7  882.76  5037.4  884.38  5046.3  885.76
  5060.2  886.81  5093.4  888.08  5095.1  888.09  5127.9  898.84  5132.4  899.61
#Mann= 7 ,-1,0
    4589      .1       0  4639.5     .04       0  4878.3      .1       0
    4944    .045       0  5046.3      .1       0  5060.2    .015       0
  5093.4      .1       0
#XS Ineff= 3 ,-1
    4711  4901.5  887.53  4901.5    4944   885.8  5046.3    5070  887.28
Permanent Ineff=
       T       T       T
Bank Sta=4944,5046.3
XS Rating Curve= 0 ,0
Exp/Cntr=0.5,0.3

Type RM Length L Ch R = 3 ,5184.6  ,,,
Bridge Culvert--1,0,-1,-1, 0
Deck Dist Width WeirC Skew NumUp NumDn MinLoCord MaxHiCord MaxSubmerge Is_Ogee
6.6,20,2.6,0, 59, 59, , , 0.98, 0, 2,2,,
  4566.5  4567.1  4574.8  4576.7  4582.1  4589.5  4595.9    4599  4601.1  4603.2
  4621.1  4626.6  4637.8  4640.1  4653.6  4662.4  4670.7  4673.5  4680.9  4688.3
  4697.3  4707.2  4710.7  4717.5  4727.1  4734.3  4740.1  4744.7  4754.6  4757.3
  4768.8  4775.5  4779.5  4793.5  4800.3  4817.5  4821.2  4825.9  4833.8  4836.7
    4847  4856.1  4862.3  4863.5    4864  4887.8  4903.7  4924.3  4941.6  4948.6
  4948.6  4960.6  4960.6  5041.9  5041.9  5053.9  5053.9  5065.9    5200
     900  899.81  898.21  897.72  896.87  895.93  894.99  894.43  893.91  893.54
  892.27  891.53  890.47  890.41  889.62   889.3  888.85  888.81  888.16  887.95
  887.47  887.11  887.09  886.74  886.58  886.57  886.34  886.31  886.05  886.17
  885.93  885.91  885.98  885.77  885.95  885.74  885.93  885.97   885.7  885.53
  886.07  886.16   886.4  886.36  886.16  885.81  885.78  885.22  885.11   884.8
   887.4   887.7   888.6   890.9     890   890.3   887.7  887.17   887.2
                                                                                
                                                                                
                                                                                
                                                                                
                                                                                
                  883.44  885.74
  4566.5  4567.1  4574.8  4576.7  4582.1  4589.5  4595.9    4599  4601.1  4603.2
  4621.1  4626.6  4637.8  4640.1  4653.6  4662.4  4670.7  4673.5  4680.9  4688.3
  4697.3  4707.2  4710.7  4717.5  4727.1  4734.3  4740.1  4744.7  4754.6  4757.3
  4768.8  4775.5  4779.5  4793.5  4800.3  4817.5  4821.2  4825.9  4833.8  4836.7
    4847  4856.1  4862.3  4863.5    4864  4887.8  4903.7  4924.3  4941.6  4948.6
  4948.6  4960.6  4960.6  5041.9  5041.9  5053.9  5053.9  5065.9    5200
     900  899.81  898.21  897.72  896.87  895.93  894.99  894.43  893.91  893.54
  892.27  891.53  890.47  890.41  889.62   889.3  888.85  888.81  888.16  887.95
  887.47  887.11  887.09  886.74  886.58  886.57  886.34  886.31  886.05  886.17
  885.93  885.91  885.98  885.77  885.95  885.74  885.93  885.97   885.7  885.53
  886.07  886.16   886.4  886.36  886.16  885.81  885.78  885.22  885.11   884.8
   887.4   887.7   888.6   890.9     890   890.3   887.7  887.17   887.2
                                                                                
                                                                                
                                                                                
                                                                                
                                                                                
                  883.44  885.74
Pier Skew, UpSta & Num, DnSta & Num=  ,4985.9, 4 ,4985.9, 4 , 3 , 3 , 0 ,,
       2       2       3       3
     875  882.11  882.11  884.15
       2       2       3       3
     875  882.11  882.11  884.15
Pier Skew, UpSta & Num, DnSta & Num=  ,5017.1, 4 ,5017.1, 4 , 3 , 3 , 0 ,,
       2       2       3       3
     875  882.99  882.99  885.03
       2       2       3       3
     875  882.99  882.99  885.03
Abutment Skew #Up #Dn= , 4 , 4
  4960.6  4961.6  4961.6  5001.6
  883.44  883.44  882.01  862.01
  4960.6  4961.6  4961.6  5001.6
  883.44  883.44  882.01  862.01
Abutment Skew #Up #Dn= , 4 , 4
  5000.9  5040.9  5040.9  5041.9
  863.37  883.37  885.74  885.74
  5000.9  5040.9  5040.9  5041.9
  863.37  883.37  885.74  885.74
BR Coef=-1 , 1 , 0 ,1.05, 0 ,,,0.8,0,1.2,0,
WSPro=,,,, 1 ,,,, 0 ,,,, 0 ,,,,-1 ,-1 ,-1 , 0 , 0 , 0 , 0 , 0
BR U #Sta/Elev= 30
  4588.4     900  4594.6  897.78  4600.2  896.55  4615.6  894.95  4624.6  893.34
  4639.8  892.37  4664.4  890.12  4733.5   886.8  4811.7   885.8  4854.2  885.74
    4879  886.54  4898.6  887.12  4947.4  885.89  4957.6  885.12  4960.6  879.12
  4967.1     879 4968.33   876.2  4976.9  874.61  5002.4  874.02    5024  876.38
 5033.37   876.2 5035.19     879  5041.9  879.13  5045.2  886.42  5053.7  886.81
  5067.5  887.55  5091.4  887.84  5093.6  887.75  5127.4  898.73  5131.4  899.61
BR U #Mann= 7
  4588.4      .1  4639.8     .04    4879      .1  4957.6    .045  5045.2      .1
  5053.7    .015  5091.4      .1
BR U Banks=4957.6,5045.2
BR D #Sta/Elev= 30
  4593.1     900  4597.3  898.71  4607.5  897.18  4617.8  894.78  4634.6  892.82
  4658.1  890.48    4672  889.56  4734.9  886.92  4803.8  885.63    4847     886
  4858.9  885.54  4890.9   885.5  4953.9  884.25  4960.6  879.15 4968.17     879
  4970.5  877.74  4972.7  877.54  4981.4  877.02  4998.6  876.71  5012.1  876.83
  5029.8  877.94 5032.71     879  5041.9  879.18  5042.6  885.15  5049.5  885.58
  5081.7  886.22    5084  886.55  5114.6  895.04  5121.7  897.35  5132.5  899.88
BR D #Mann= 6
  4593.1      .1  4634.6     .04  4890.9     .02  4953.9      .1  4960.6    .045
  5042.6      .1
BR D Banks=4953.9,5042.6
BC Design=,, 0 ,, 0 ,,,,,,
BC Use User HTab Curves=0
BC User HTab FreeFlow(D)= 0

Type RM Length L Ch R = 1 ,5167.9  ,40,40,40
XS GIS Cut Line= 2
      187180.212      592410.067      187653.156      592671.855
#Sta/Elev= 30
  4593.2  900.01  4598.7  898.48  4605.1  897.51  4611.1  896.09    4626  893.69
  4634.6   892.7  4658.2  890.44  4673.6  889.41    4698  888.65  4741.5  886.69
  4805.9  885.64  4846.3  885.95  4901.7   885.2  4926.1  884.88  4952.2  884.09
  4961.6  883.57  4965.4  882.31  4968.2  879.35  4970.9  877.83  4984.3  876.61
  4991.7   876.6  5011.1   876.9  5032.4  879.02  5033.9   880.5  5035.4  881.48
  5042.6  884.61  5048.4  885.31  5081.3  886.09  5084.3  886.52  5133.8     900
#Mann= 6 ,-1,0
  4593.2      .1       0  4634.6     .04       0  4901.7     .02       0
  4952.2      .1       0  4961.6    .045       0  5042.6      .1       0
#XS Ineff= 3 ,-1
    4785    4847     886    4847  4953.9  884.79  5042.6    5083  886.12
Permanent Ineff=
       T       T       T
Bank Sta=4961.6,5042.6
XS Rating Curve= 0 ,0
Exp/Cntr=0.5,0.3

Type RM Length L Ch R = 1 ,5127.9  ,50.1,50.1,50.1
XS GIS Cut Line= 4
      187169.759         592450.      187598.308      592687.214
      187598.308      592687.214      187647.027      592699.763
#Sta/Elev= 30
  4603.7  899.99  4614.5  898.24  4639.3  892.24  4661.8  890.05  4675.7  889.18
  4702.5  888.67  4708.7   888.1  4738.3  887.05  4771.9  886.34  4816.9   885.6
  4872.9  885.26  4873.8  884.56  4912.4  884.47  4930.4     884  4969.5   883.7
  4975.9  879.05  4979.4  877.95  4990.3  877.37  5026.6  878.47  5029.4  879.16
  5036.2  882.96  5050.4  884.21  5085.2  884.87  5088.1  884.46  5108.1  885.78
    5113  887.11  5121.2  891.24  5129.2  893.96    5138  897.94  5142.9  899.73
#Mann= 5 ,-1,0
  4603.7     .04       0  4912.4    .015       0  4930.4      .1       0
  4969.5    .045       0  5036.2      .1       0
#XS Ineff= 2 ,-1
    4690  4702.5  888.67    4813  4839.5  885.66
Permanent Ineff=
       T       T
Bank Sta=4969.5,5036.2
XS Rating Curve= 0 ,0
Exp/Cntr=0.3,0.1

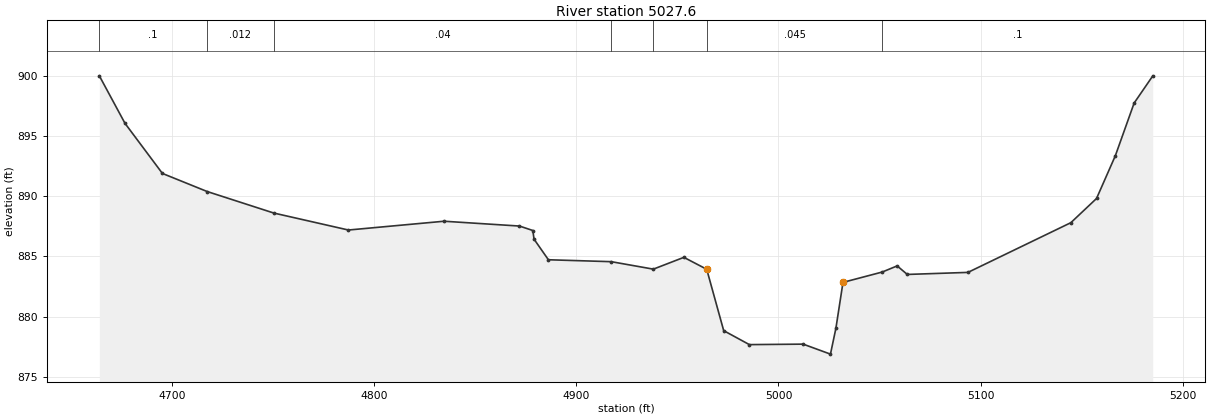
Type RM Length L Ch R = 1 ,5027.6  ,,,
XS GIS Cut Line= 6
      187163.172      592587.251      187222.868      592593.695
      187222.868      592593.695      187602.271      592803.705
      187602.271      592803.705       187628.64      592811.271
#Sta/Elev= 30
  4664.1     900  4676.8  896.05  4695.3  891.89  4717.4  890.39  4750.4   888.6
  4787.3  887.19  4834.6  887.92  4871.9  887.52  4878.5  887.15  4879.1  886.43
  4886.2  884.72  4917.3  884.56  4938.1  883.94  4953.2  884.92  4964.5  883.93
  4972.9  878.83  4985.6  877.67  5012.2  877.71  5025.7  876.88  5028.4  879.03
  5031.9  882.84  5051.3   883.7  5058.7  884.21  5063.7   883.5  5093.7  883.67
  5144.6   887.8  5157.3  889.81  5166.6  893.36  5175.9  897.74  5185.1  899.99
#Mann= 7 ,-1,0
  4664.1      .1       0  4717.4    .012       0  4750.4     .04       0
  4917.3    .015       0  4938.1      .1       0  4964.5    .045       0
  5051.3      .1       0
#XS Ineff= 2 ,-1
    4778  4871.9  887.52  5058.7    5101  884.21
Permanent Ineff=
       T       T
Bank Sta=4964.5,5031.9
XS Rating Curve= 0 ,0
Exp/Cntr=0.3,0.1
LCMann Table=0

--- Wheeling Creek.g03 (geometry) ---

Geom Title=Proposed + 2'
Program Version=6.20

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
River Reach=Wheeling Creek  ,Wheeling Creek

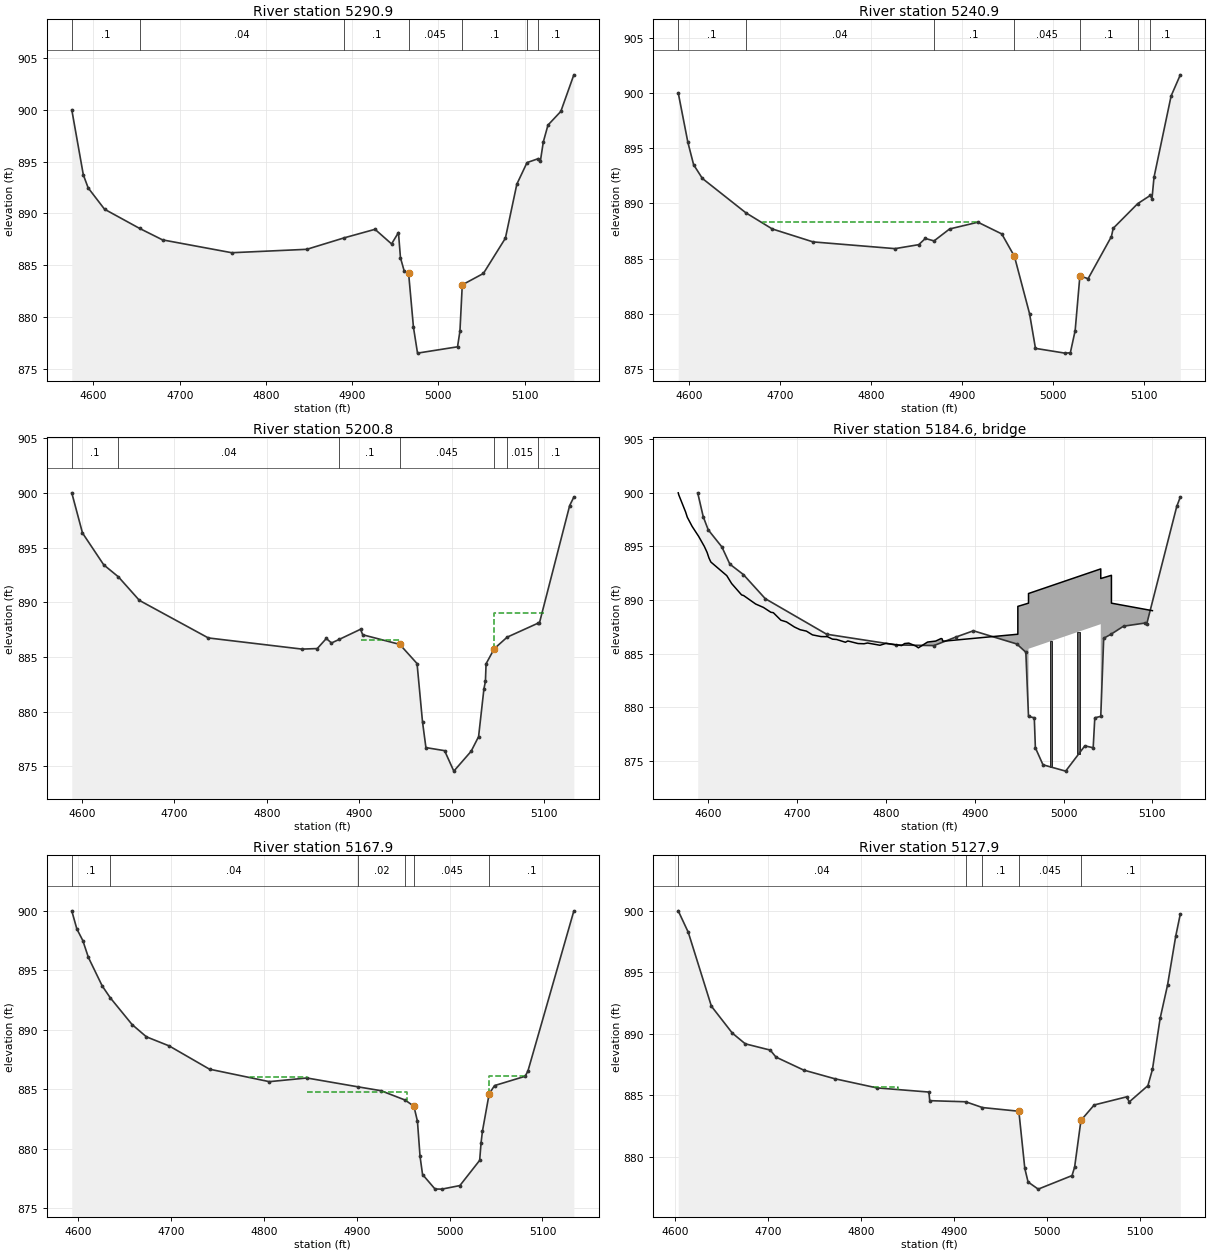
Type RM Length L Ch R = 1 ,5290.9  ,49.9,49.9,49.9
XS GIS Cut Line= 2
      187228.999      592296.785      187739.119      592579.151
#Sta/Elev= 30
  4574.8  900.01  4588.2  893.73  4593.8  892.47  4612.8  890.41  4653.4  888.56
  4680.1  887.45  4760.4  886.21  4847.4  886.54  4890.9  887.65  4926.5  888.47
  4945.7  887.06  4953.7  888.16    4956  885.73  4960.4  884.43  4965.4  884.28
  4971.1  879.01  4975.8  876.52  5022.2  877.13    5025  878.65  5027.7  883.11
  5052.2  884.21  5077.7  887.61    5091  892.83  5102.8  894.91  5115.9  895.29
  5118.3  895.06  5121.7  896.91  5127.1  898.53    5142  899.85  5157.1  903.38
#Mann= 7 ,-1,0
  4574.8      .1       0  4653.4     .04       0  4890.9      .1       0
  4965.4    .045       0  5027.7      .1       0  5102.8    .015       0
  5115.9      .1       0
#XS Ineff= 2 ,-1
    4654  4926.5  888.47  4926.5  4953.7  888.16
Permanent Ineff=
       T       F
Bank Sta=4965.4,5027.7
XS Rating Curve= 0 ,0
Exp/Cntr=0.3,0.1

Type RM Length L Ch R = 1 ,5240.9  ,40.1,40.1,40.1
XS GIS Cut Line= 2
      187213.715      592345.207       187699.34      592614.014
#Sta/Elev= 30
  4588.5     900  4599.1  895.52  4605.4   893.5    4615  892.26  4662.8  889.15
  4691.8  887.69  4736.6  886.52  4826.6  885.91  4852.7  886.27  4859.9  886.83
  4869.5  886.61  4886.6  887.69  4917.7   888.3  4943.9  887.24  4957.8  885.21
  4974.4  880.03  4980.9  876.89  5013.2  876.46  5019.2  876.49  5024.5   878.5
  5029.7  883.45  5038.7  883.19  5064.3     887  5066.3  887.75  5093.2  889.98
    5107  890.72  5108.9  890.43  5111.1  892.36  5129.9  899.72    5140  901.63
#Mann= 7 ,-1,0
  4588.5      .1       0  4662.8     .04       0  4869.5      .1       0
  4957.8    .045       0  5029.7      .1       0  5093.2    .015       0
    5107      .1       0
#XS Ineff= 2 ,-1
    4682  4916.5  888.31  4916.5  4933.2  887.49
Permanent Ineff=
       T       T
Bank Sta=4957.8,5029.7
XS Rating Curve= 0 ,0
Exp/Cntr=0.5,0.3

Type RM Length L Ch R = 1 ,5200.8  ,33,33,33
XS GIS Cut Line= 2
      187192.751      592379.322       187668.22      592642.508
#Sta/Elev= 30
    4589     900  4600.6  896.33  4623.6  893.42  4639.5  892.32  4662.2  890.17
  4736.8  886.74  4838.2  885.72  4854.7  885.77  4864.5  886.69  4870.1  886.28
  4878.3   886.6  4901.5  887.53  4903.9  887.03    4944  886.15  4962.7   884.4
  4968.6  879.08  4972.3  876.72  4992.5  876.44  5002.5  874.57  5021.2  876.38
  5029.3  877.72  5035.1   882.1  5036.7  882.76  5037.4  884.38  5046.3  885.76
  5060.2  886.81  5093.4  888.08  5095.1  888.09  5127.9  898.84  5132.4  899.61
#Mann= 7 ,-1,0
    4589      .1       0  4639.5     .04       0  4878.3      .1       0
    4944    .045       0  5046.3      .1       0  5060.2    .015       0
  5093.4      .1       0
#XS Ineff= 3 ,-1
    4711  4901.5  887.53  4901.5    4944  886.55  5046.3    5100  889.04
Permanent Ineff=
       T       T       T
Bank Sta=4944,5046.3
XS Rating Curve= 0 ,0
Exp/Cntr=0.5,0.3

Type RM Length L Ch R = 3 ,5184.6  ,,,
Bridge Culvert--1,0,-1,-1, 0
Deck Dist Width WeirC Skew NumUp NumDn MinLoCord MaxHiCord MaxSubmerge Is_Ogee
6.6,20,2.6,0, 55, 55, , , 0.98, 0, 2,2,,
  4566.5  4567.1  4574.8  4576.7  4582.1  4589.5  4595.9    4599  4601.1  4603.2
  4621.1  4626.6  4637.8  4640.1  4653.6  4662.4  4670.7  4673.5    4682  4688.3
  4697.3  4703.7  4710.7  4717.5  4727.1  4734.3  4740.1  4744.7  4754.6  4757.3
  4768.8  4775.5  4779.5  4793.5  4800.3  4817.8  4821.2  4825.9  4833.8  4836.7
    4847  4856.1  4862.3  4863.5    4864    4865  4948.6  4948.6  4960.6  4960.6
  5041.9  5041.9  5053.9  5053.9    5100
     900  899.81  898.21  897.72  896.87  895.93  894.99  894.43  893.91  893.54
  892.27  891.53  890.47  890.41  889.62   889.3  888.85  888.81  888.11  887.95
  887.47  887.22  887.09  886.74  886.58  886.57  886.34  886.31  886.05  886.17
  885.93  885.91  885.98  885.77  885.95  885.74  885.93  885.97   885.7  885.53
  886.07  886.16   886.4  886.36  886.16  886.15   886.8   889.4   889.7   890.6
   892.9     892   892.3   889.7     889
                                                                                
                                                                                
                                                                                
                                                                                
                                                                          885.44
  887.74
  4566.5  4567.1  4574.8  4576.7  4582.1  4589.5  4595.9    4599  4601.1  4603.2
  4621.1  4626.6  4637.8  4640.1  4653.6  4662.4  4670.7  4673.5    4682  4688.3
  4697.3  4703.7  4710.7  4717.5  4727.1  4734.3  4740.1  4744.7  4754.6  4757.3
  4768.8  4775.5  4779.5  4793.5  4800.3  4817.8  4821.2  4825.9  4833.8  4836.7
    4847  4856.1  4862.3  4863.5    4864    4865  4948.6  4948.6  4960.6  4960.6
  5041.9  5041.9  5053.9  5053.9    5100
     900  899.81  898.21  897.72  896.87  895.93  894.99  894.43  893.91  893.54
  892.27  891.53  890.47  890.41  889.62   889.3  888.85  888.81  888.11  887.95
  887.47  887.22  887.09  886.74  886.58  886.57  886.34  886.31  886.05  886.17
  885.93  885.91  885.98  885.77  885.95  885.74  885.93  885.97   885.7  885.53
  886.07  886.16   886.4  886.36  886.16  886.15   886.8   889.4   889.7   890.6
   892.9     892   892.3   889.7     889
                                                                                
                                                                                
                                                                                
                                                                                
                                                                          885.44
  887.74
Pier Skew, UpSta & Num, DnSta & Num=  ,4985.9, 4 ,4985.9, 4 , 3 , 3 , 0 ,,
       2       2       3       3
     875  884.11  884.11  886.15
       2       2       3       3
     875  884.11  884.11  886.15
Pier Skew, UpSta & Num, DnSta & Num=  ,5017.1, 4 ,5017.1, 4 , 3 , 3 , 0 ,,
       2       2       3       3
     875  884.99  884.99  887.03
       2       2       3       3
     875  884.99  884.99  887.03
Abutment Skew #Up #Dn= , 4 , 4
  4960.6  4961.6  4961.6  5001.6
  885.46  885.46  884.06  864.06
  4960.6  4961.6  4961.6  5001.6
  885.46  885.46  884.06  864.06
Abutment Skew #Up #Dn= , 4 , 4
  5000.9  5040.9  5040.9  5041.9
  865.37  885.37  887.74  887.74
  5000.9  5040.9  5040.9  5041.9
  865.37  885.37  887.74  887.74
BR Coef=-1 , 1 , 0 ,1.05, 0 ,,,0.8,0,1.2,0,
WSPro=,,,, 1 ,,,, 0 ,,,, 0 ,,,,-1 ,-1 ,-1 , 0 , 0 , 0 , 0 , 0
BR U #Sta/Elev= 30
  4588.4     900  4594.6  897.78  4600.2  896.55  4615.6  894.95  4624.6  893.34
  4639.8  892.37  4664.4  890.12  4733.5   886.8  4811.7   885.8  4854.2  885.74
    4879  886.54  4898.6  887.12  4947.4  885.89  4957.6  885.12  4960.6  879.12
  4967.1     879 4968.33   876.2  4976.9  874.61  5002.4  874.02    5024  876.38
 5033.37   876.2 5035.19     879  5041.9  879.13  5045.2  886.42  5053.7  886.81
  5067.5  887.55  5091.4  887.84  5093.6  887.75  5127.4  898.73  5131.4  899.61
BR U #Mann= 7
  4588.4      .1  4639.8     .04    4879      .1  4957.6    .045  5045.2      .1
  5053.7    .015  5091.4      .1
BR U Banks=4957.6,5045.2
BR D #Sta/Elev= 30
  4593.1     900  4597.3  898.71  4607.5  897.18  4617.8  894.78  4634.6  892.82
  4658.1  890.48    4672  889.56  4734.9  886.92  4803.8  885.63    4847     886
  4858.9  885.54  4890.9   885.5  4953.9  884.25  4960.6  879.15 4968.17     879
  4970.5  877.74  4972.7  877.54  4981.4  877.02  4998.6  876.71  5012.1  876.83
  5029.8  877.94 5032.71     879  5041.9  879.18  5042.6  885.15  5049.5  885.58
  5081.7  886.22    5084  886.55  5114.6  895.04  5121.7  897.35  5132.5  899.88
BR D #Mann= 6
  4593.1      .1  4634.6     .04  4890.9     .02  4953.9      .1  4960.6    .045
  5042.6      .1
BR D Banks=4953.9,5042.6
BC Design=,, 0 ,, 0 ,,,,,,
BC Use User HTab Curves=0
BC User HTab FreeFlow(D)= 0

Type RM Length L Ch R = 1 ,5167.9  ,40,40,40
XS GIS Cut Line= 2
      187180.212      592410.067      187653.156      592671.855
#Sta/Elev= 30
  4593.2  900.01  4598.7  898.48  4605.1  897.51  4611.1  896.09    4626  893.69
  4634.6   892.7  4658.2  890.44  4673.6  889.41    4698  888.65  4741.5  886.69
  4805.9  885.64  4846.3  885.95  4901.7   885.2  4926.1  884.88  4952.2  884.09
  4961.6  883.57  4965.4  882.31  4968.2  879.35  4970.9  877.83  4984.3  876.61
  4991.7   876.6  5011.1   876.9  5032.4  879.02  5033.9   880.5  5035.4  881.48
  5042.6  884.61  5048.4  885.31  5081.3  886.09  5084.3  886.52  5133.8     900
#Mann= 6 ,-1,0
  4593.2      .1       0  4634.6     .04       0  4901.7     .02       0
  4952.2      .1       0  4961.6    .045       0  5042.6      .1       0
#XS Ineff= 3 ,-1
    4785    4847     886    4847  4953.9  884.79  5042.6    5083  886.12
Permanent Ineff=
       T       T       T
Bank Sta=4961.6,5042.6
XS Rating Curve= 0 ,0
Exp/Cntr=0.5,0.3

Type RM Length L Ch R = 1 ,5127.9  ,50.1,50.1,50.1
XS GIS Cut Line= 4
      187169.759         592450.      187598.308      592687.214
      187598.308      592687.214      187647.027      592699.763
#Sta/Elev= 30
  4603.7  899.99  4614.5  898.24  4639.3  892.24  4661.8  890.05  4675.7  889.18
  4702.5  888.67  4708.7   888.1  4738.3  887.05  4771.9  886.34  4816.9   885.6
  4872.9  885.26  4873.8  884.56  4912.4  884.47  4930.4     884  4969.5   883.7
  4975.9  879.05  4979.4  877.95  4990.3  877.37  5026.6  878.47  5029.4  879.16
  5036.2  882.96  5050.4  884.21  5085.2  884.87  5088.1  884.46  5108.1  885.78
    5113  887.11  5121.2  891.24  5129.2  893.96    5138  897.94  5142.9  899.73
#Mann= 5 ,-1,0
  4603.7     .04       0  4912.4    .015       0  4930.4      .1       0
  4969.5    .045       0  5036.2      .1       0
#XS Ineff= 2 ,-1
    4690  4702.5  888.67    4813  4839.5  885.66
Permanent Ineff=
       T       T
Bank Sta=4969.5,5036.2
XS Rating Curve= 0 ,0
Exp/Cntr=0.3,0.1

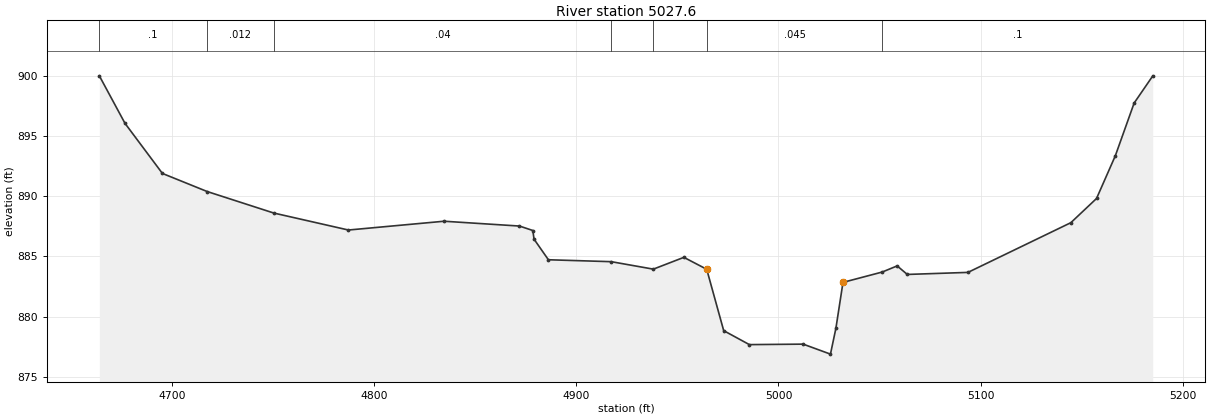
Type RM Length L Ch R = 1 ,5027.6  ,,,
XS GIS Cut Line= 6
      187163.172      592587.251      187222.868      592593.695
      187222.868      592593.695      187602.271      592803.705
      187602.271      592803.705       187628.64      592811.271
#Sta/Elev= 30
  4664.1     900  4676.8  896.05  4695.3  891.89  4717.4  890.39  4750.4   888.6
  4787.3  887.19  4834.6  887.92  4871.9  887.52  4878.5  887.15  4879.1  886.43
  4886.2  884.72  4917.3  884.56  4938.1  883.94  4953.2  884.92  4964.5  883.93
  4972.9  878.83  4985.6  877.67  5012.2  877.71  5025.7  876.88  5028.4  879.03
  5031.9  882.84  5051.3   883.7  5058.7  884.21  5063.7   883.5  5093.7  883.67
  5144.6   887.8  5157.3  889.81  5166.6  893.36  5175.9  897.74  5185.1  899.99
#Mann= 7 ,-1,0
  4664.1      .1       0  4717.4    .012       0  4750.4     .04       0
  4917.3    .015       0  4938.1      .1       0  4964.5    .045       0
  5051.3      .1       0
#XS Ineff= 2 ,-1
    4778  4871.9  887.52  5058.7    5101  884.21
Permanent Ineff=
       T       T
Bank Sta=4964.5,5031.9
XS Rating Curve= 0 ,0
Exp/Cntr=0.3,0.1
LCMann Table=0

--- Wheeling Creek.g04 (geometry) ---

Geom Title=Proposed + 2' + VA
Program Version=6.20

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
River Reach=Wheeling Creek  ,Wheeling Creek

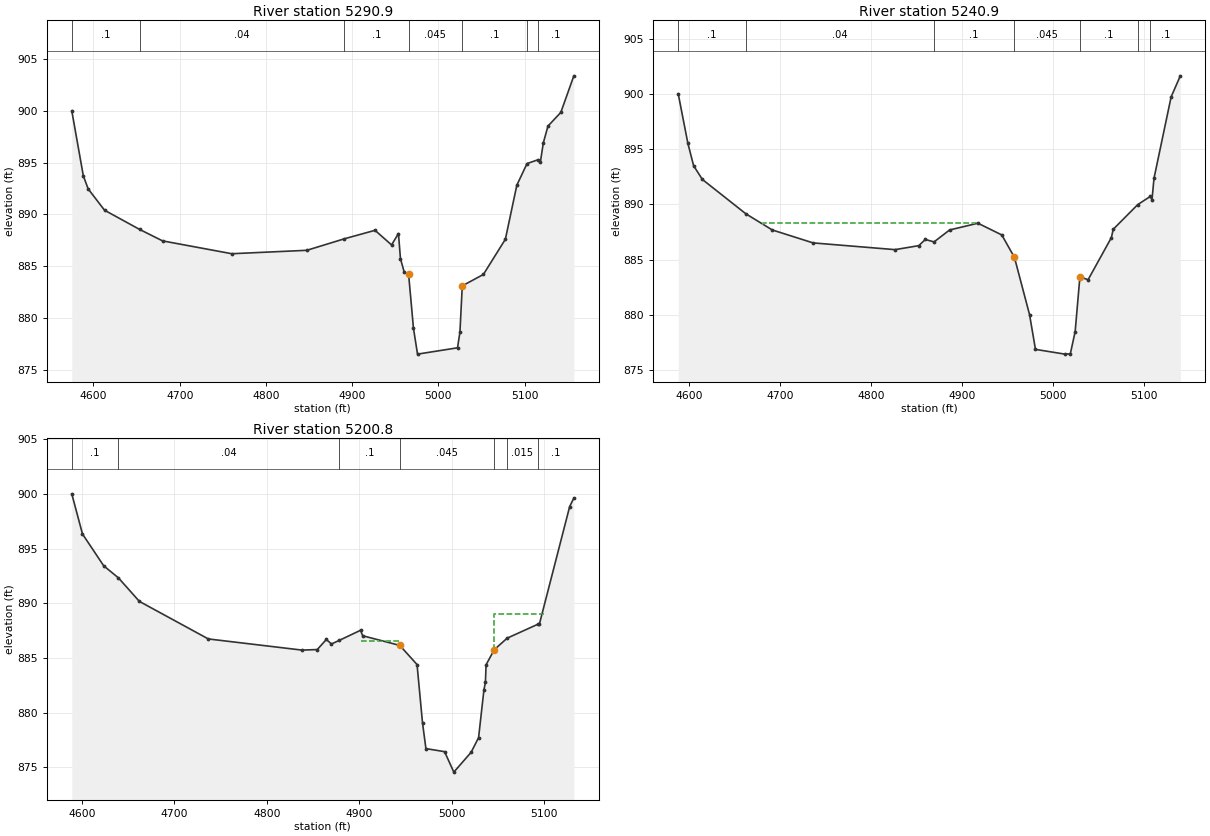
Type RM Length L Ch R = 1 ,5290.9  ,49.9,49.9,49.9
XS GIS Cut Line= 2
      187228.999      592296.785      187739.119      592579.151
#Sta/Elev= 30
  4574.8  900.01  4588.2  893.73  4593.8  892.47  4612.8  890.41  4653.4  888.56
  4680.1  887.45  4760.4  886.21  4847.4  886.54  4890.9  887.65  4926.5  888.47
  4945.7  887.06  4953.7  888.16    4956  885.73  4960.4  884.43  4965.4  884.28
  4971.1  879.01  4975.8  876.52  5022.2  877.13    5025  878.65  5027.7  883.11
  5052.2  884.21  5077.7  887.61    5091  892.83  5102.8  894.91  5115.9  895.29
  5118.3  895.06  5121.7  896.91  5127.1  898.53    5142  899.85  5157.1  903.38
#Mann= 7 ,-1,0
  4574.8      .1       0  4653.4     .04       0  4890.9      .1       0
  4965.4    .045       0  5027.7      .1       0  5102.8    .015       0
  5115.9      .1       0
#XS Ineff= 2 ,-1
    4654  4926.5  888.47  4926.5  4953.7  888.16
Permanent Ineff=
       T       F
Bank Sta=4965.4,5027.7
XS Rating Curve= 0 ,0
Exp/Cntr=0.3,0.1

Type RM Length L Ch R = 1 ,5240.9  ,40.1,40.1,40.1
XS GIS Cut Line= 2
      187213.715      592345.207       187699.34      592614.014
#Sta/Elev= 30
  4588.5     900  4599.1  895.52  4605.4   893.5    4615  892.26  4662.8  889.15
  4691.8  887.69  4736.6  886.52  4826.6  885.91  4852.7  886.27  4859.9  886.83
  4869.5  886.61  4886.6  887.69  4917.7   888.3  4943.9  887.24  4957.8  885.21
  4974.4  880.03  4980.9  876.89  5013.2  876.46  5019.2  876.49  5024.5   878.5
  5029.7  883.45  5038.7  883.19  5064.3     887  5066.3  887.75  5093.2  889.98
    5107  890.72  5108.9  890.43  5111.1  892.36  5129.9  899.72    5140  901.63
#Mann= 7 ,-1,0
  4588.5      .1       0  4662.8     .04       0  4869.5      .1       0
  4957.8    .045       0  5029.7      .1       0  5093.2    .015       0
    5107      .1       0
#XS Ineff= 2 ,-1
    4682  4916.5  888.31  4916.5  4933.2  887.49
Permanent Ineff=
       T       T
Bank Sta=4957.8,5029.7
XS Rating Curve= 0 ,0
Exp/Cntr=0.5,0.3

Type RM Length L Ch R = 1 ,5200.8  ,33,33,33
XS GIS Cut Line= 2
      187192.751      592379.322       187668.22      592642.508
#Sta/Elev= 30
    4589     900  4600.6  896.33  4623.6  893.42  4639.5  892.32  4662.2  890.17
  4736.8  886.74  4838.2  885.72  4854.7  885.77  4864.5  886.69  4870.1  886.28
  4878.3   886.6  4901.5  887.53  4903.9  887.03    4944  886.15  4962.7   884.4
  4968.6  879.08  4972.3  876.72  4992.5  876.44  5002.5  874.57  5021.2  876.38
  5029.3  877.72  5035.1   882.1  5036.7  882.76  5037.4  884.38  5046.3  885.76
  5060.2  886.81  5093.4  888.08  5095.1  888.09  5127.9  898.84  5132.4  899.61
#Mann= 7 ,-1,0
    4589      .1       0  4639.5     .04       0  4878.3      .1       0
    4944    .045       0  5046.3      .1       0  5060.2    .015       0
  5093.4      .1       0
#XS Ineff= 3 ,-1
    4711  4901.5  887.53  4901.5    4944  886.55  5046.3    5100  889.04
Permanent Ineff=
       T       T       T
Bank Sta=4944,5046.3
XS Rating Curve= 0 ,0
Exp/Cntr=0.5,0.3